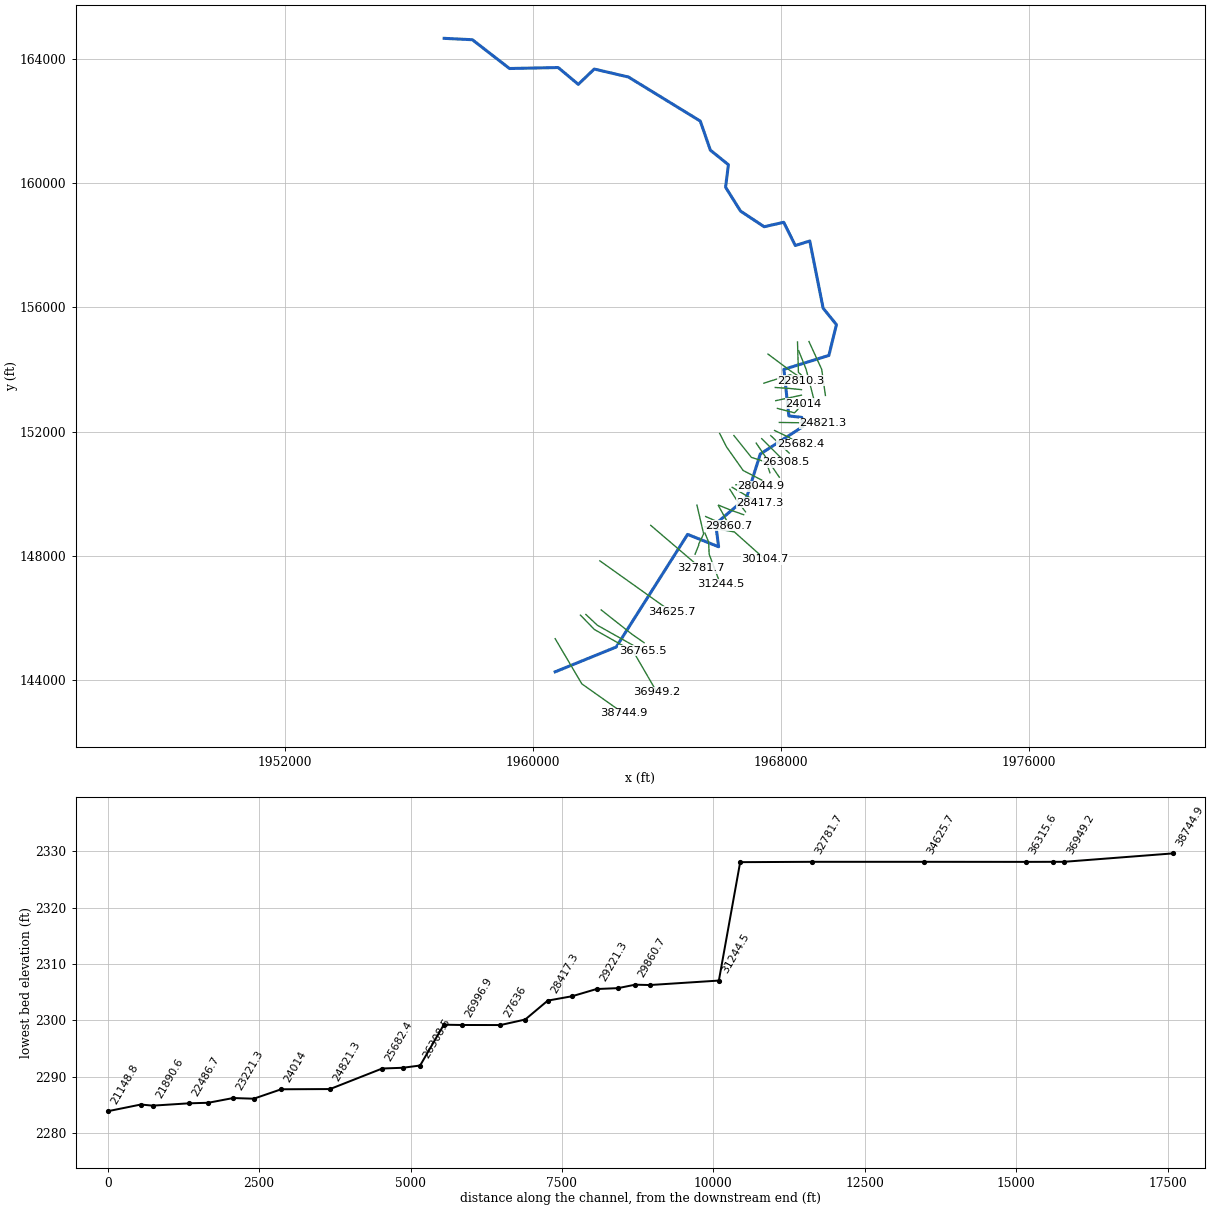
--- LrlCrk2.prj (project) ---

Proj Title=LrlCrk2
Current Plan=p01
Default Exp/Contr=0,0
English Units
Geom File=g01
Flow File=f01
Plan File=p01
BEGIN DESCRIPTION:
END DESCRIPTION:
DSS Export Rating Curves= 0
DSS Export Rating Curve Sorted= 0
DSS Export Volume Flow Curves= 0
DXF OffsetX= 0
DXF OffsetY= 0
DXF ScaleX= 0
DXF ScaleY= 0

--- LrlCrk2.p01 (plan) ---

Plan Title=Floodplain
Program Version=4.00
Geom File=g01
Flow File=f01
K Sum by GR=0
Std Step Tol=0.01
Critical Tol=0.01
Num of Std Step Trials=20
Max Error Tol=0.3
Flow Tol Ratio=0.001
Split Flow NTrial=30
Split Flow Tol=0.02
Split Flow Ratio=0.02
Log Output Level=0
Friction Slope Method=1
Unsteady Friction Slope Method=2
Unsteady Bridges Friction Slope Method=1
Global Log Level=0
CheckData=False
Run HTab=0
Run UNet=0
Run PostProcess=0
UNET Theta=0
UNET Theta Warmup=0
UNET ZTol=0
UNET ZSATol=0
UNET MxIter=0
UNET MaxInSteps=0
UNET DtIC=0
UNET DtMin=0
UNET MaxCRTS=0
UNET WFStab=0
UNET SFStab=0
UNET WFX=0
UNET SFX=0
UNET DSS MLevel=0
UNET DZMax Abort=0
UNET Convert EG Bridges=0
UNET Use Existing IB Tables=0
UNET Froude Limit=0
UNET Froude Power=0
Write IC File=0
Echo Input=False
Echo Output=False
Write Detailed=0

--- LrlCrk2.f01 (steady flow) ---

Flow Title=NFF Regression Equation
Program Version=4.00
Number of Profiles=1
Profile Names=P100yr
River Rch & RM=LrlCrk2,Main      ,38744.9
454.0624
River Rch & RM=LrlCrk2,Main      ,36765.5
987.5373
River Rch & RM=LrlCrk2,Main      ,34625.7
1034.766
River Rch & RM=LrlCrk2,Main      ,32781.7
1110.604
River Rch & RM=LrlCrk2,Main      ,30104.7
1222.009
River Rch & RM=LrlCrk2,Main      ,26699.1
1330.928
River Rch & RM=LrlCrk2,Main      ,20822
1463.232
River Rch & RM=LrlCrk2,Main      ,19199
1622.205
River Rch & RM=LrlCrk2,Main      ,18821.3
2136.351
River Rch & RM=LrlCrk2,Main      ,16082.7
2255.945
River Rch & RM=LrlCrk2,Main      ,13561.4
2403.602
River Rch & RM=LrlCrk2,Main      ,8912.9
2564.282
River Rch & RM=LrlCrk2,Main      ,231.6
2846.050
Boundary for River Rch & Prof#=LrlCrk2,Main      ,1
Up Type=0
Dn Type=3
Dn Slope=0.017522

--- LrlCrk2.g01 (geometry) ---

Geom Title=USGS 3m DEM
Program Version=4.10

River Reach=LrlCrk2         ,Main
Reach XY= 30
     1960718.207      144259.576     1962687.241      145059.356
     1964988.611      148687.445     1965988.772      148288.659
      1965893.22      149027.052     1966890.242      149874.766
     1967331.331      151277.082     1968706.708       152161.47
     1968668.947      152455.741     1968252.502      152503.011
     1968093.429      154003.812     1969543.085      154452.364
     1969786.514      155444.969     1969357.951      155974.907
     1968926.831      158138.884     1968460.166      157993.289
     1968086.493      158741.846     1967458.091      158598.202
     1966696.139      159100.887     1966212.578      159872.014
     1966304.378      160596.753     1965722.972      161064.406
     1965396.812      162002.616     1963081.381       163421.09
     1961979.042      163677.925     1961463.157      163185.164
     1960816.907      163726.813      1959245.77      163695.324
     1958050.458      164622.408     1957139.623       164667.49

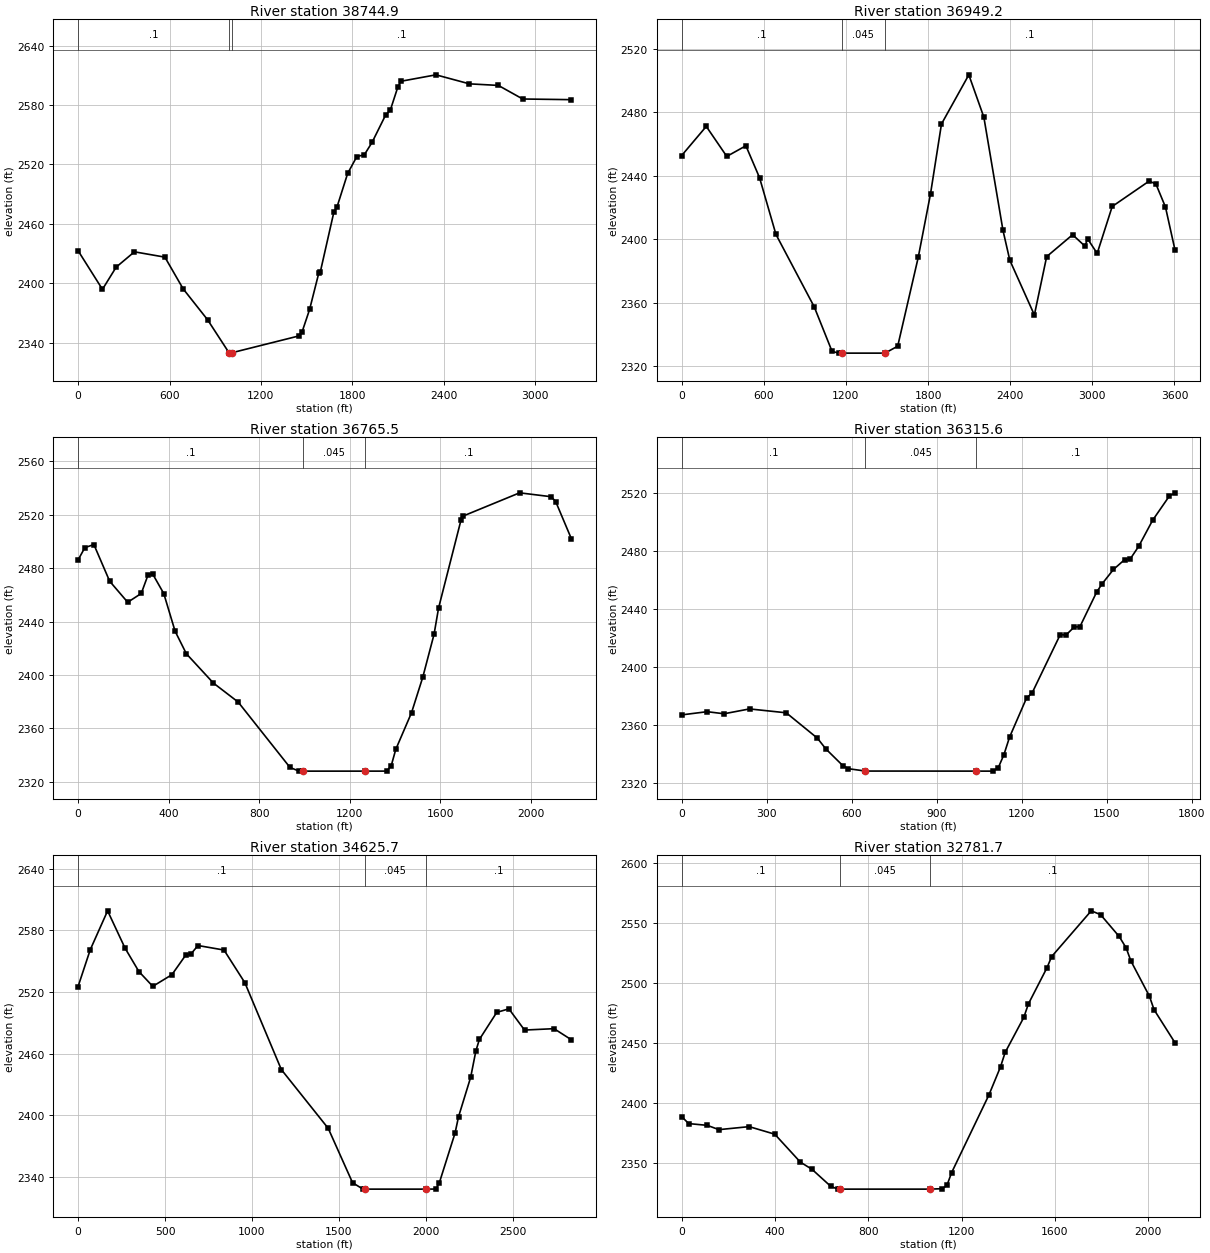
Type RM Length L Ch R = 1 ,38744.9 ,1781.7,1795.2,1808.6
XS GIS Cut Line= 3
     1960719.106      145327.454     1961578.055      143872.967
     1962924.846      142921.558
#Sta/Elev= 30
       0 2432.97   159.9 2393.97   249.9 2416.37   369.8 2431.85   569.7 2426.47
   689.7 2394.44   849.6 2363.32   989.4 2330.22   999.5 2329.59  1009.4 2329.98
  1449.3 2346.95  1469.3 2350.69  1519.3 2373.64  1579.2 2410.12  1589.2 2411.25
  1679.2 2472.34  1699.2 2477.09  1769.1 2510.97    1829 2527.89    1879 2529.92
  1928.9  2542.2  2018.8 2570.08  2048.8 2574.72  2098.8 2598.36  2118.8    2604
  2348.5  2610.5  2568.3 2601.39  2758.1 2599.81    2918  2586.1  3237.6 2585.43
#Mann= 3 , 0 , 0
       0      .1       0   989.4    .045       0  1009.4      .1       0
Bank Sta=989.4,1009.4
XS Rating Curve= 0 ,0
Exp/Cntr=0.3,0.1

Type RM Length L Ch R = 1 ,36949.2 ,184,183.6,182.2
XS GIS Cut Line= 4
     1961533.184       146087.49     1961985.166      145622.134
      1963238.69      144915.159     1964000.292       143603.83
#Sta/Elev= 30
       0 2452.83   179.6  2471.2   329.4 2452.26   469.1 2458.97   568.9 2438.81
   688.7 2403.02   968.5 2357.29  1098.5 2329.23  1148.4  2328.1  1168.4  2328.1
  1485.2  2328.1  1578.2 2332.48  1728.1  2388.5    1818 2428.66    1898 2472.71
  2097.8 2503.75  2207.6 2477.03  2347.3 2405.59  2397.2 2386.76  2576.7 2352.17
  2666.5    2389  2856.1 2402.83  2945.9 2395.64  2965.8  2400.2  3035.6 2391.04
  3145.4 2420.66  3414.8 2436.65  3464.6 2434.88  3534.5  2420.3  3604.3  2393.1
#Mann= 3 , 0 , 0
       0      .1       0  1168.4    .045       0  1485.2      .1       0
Bank Sta=1168.4,1485.2
XS Rating Curve= 0 ,0
Exp/Cntr=0.3,0.1

Type RM Length L Ch R = 1 ,36765.5 ,454.1,449.7,443.5
XS GIS Cut Line= 3
     1961709.537      146106.816     1962080.599      145759.627
     1963538.293      144942.403
#Sta/Elev= 30
       0 2486.15    29.9 2495.34    69.8 2497.66   139.5 2470.22   219.2 2454.46
     279 2461.05   308.9 2474.84   328.8 2475.83   378.6 2460.96   428.4 2432.87
   478.3 2415.94   597.7 2394.01   707.1  2379.8   935.9  2330.9   975.7  2328.1
   995.6  2328.1  1268.1  2328.1  1363.6 2328.11  1383.5 2332.29  1403.4 2344.38
    1473 2371.82  1522.8 2398.45  1572.5  2430.5  1592.4 2450.12  1691.9 2516.23
  1701.8 2519.05  1950.5 2536.36  2089.8 2533.45  2109.7 2529.86  2179.3 2501.91
#Mann= 3 , 0 , 0
       0      .1       0   995.6    .045       0  1268.1      .1       0
Bank Sta=995.6,1268.1
XS Rating Curve= 0 ,0
Exp/Cntr=0.3,0.1

Type RM Length L Ch R = 1 ,36315.6 ,1682.4,1687.5,1683.7
XS GIS Cut Line= 3
     1962202.166       146254.47     1963212.888      145457.842
     1963586.307      145198.938
#Sta/Elev= 30
       0 2366.91    89.8 2369.12   149.6 2367.68   239.4 2371.03   369.1 2368.35
   478.9 2350.85   508.8 2343.42   568.6 2331.92   588.6 2329.76   648.4 2328.14
  1037.5  2328.1  1097.4 2328.09  1117.3 2330.38  1137.3 2339.41  1157.2 2351.51
  1217.1 2378.48    1237 2382.09  1336.3 2422.37  1356.1 2421.96  1385.7  2427.6
  1405.5 2427.73  1464.7 2451.69  1484.5 2457.52    1524  2467.3  1563.5 2474.08
  1583.3 2474.57  1612.9  2483.2  1662.3 2501.27  1721.6 2518.05  1741.3 2520.19
#Mann= 3 , 0 , 0
       0      .1       0   648.4    .045       0  1037.5      .1       0
Bank Sta=648.4,1037.5
XS Rating Curve= 0 ,0
Exp/Cntr=0.3,0.1

Type RM Length L Ch R = 1 ,34625.7 ,1845.9,1843.9,1841.5
XS GIS Cut Line= 2
     1962158.875      147836.525      1964470.79      146191.369
#Sta/Elev= 30
       0 2525.37    69.9 2561.15   169.8 2599.05   269.8 2562.83   349.7 2539.96
   429.6 2525.53   539.5 2536.85   619.5 2556.02   649.4 2557.04   689.4 2565.28
   839.3 2560.87   959.2 2529.08    1169 2444.51  1438.7 2387.29  1578.6 2334.37
  1638.6  2328.1  1648.6  2328.1  2000.1  2328.1  2058.2 2328.18  2078.2 2334.48
  2168.1 2382.65  2188.1  2398.5    2258    2437    2288 2462.67    2308  2473.8
  2407.9 2500.17  2477.8 2503.63  2567.8 2482.97  2737.6 2484.32  2837.5 2473.49
#Mann= 3 , 0 , 0
       0      .1       0  1648.6    .045       0  2000.1      .1       0
Bank Sta=1648.6,2000.1
XS Rating Curve= 0 ,0
Exp/Cntr=0.3,0.1

Type RM Length L Ch R = 1 ,32781.7 ,1218.9,1183.7,1151
XS GIS Cut Line= 2
     1963800.401      148977.941     1965408.593      147603.758
#Sta/Elev= 30
       0 2388.48    29.9 2382.67   109.8  2381.2   159.6 2377.63   289.4 2380.13
   399.1 2373.84   508.9 2350.58   558.8 2344.59   638.6 2330.52   668.5  2328.1
   678.5  2328.1  1063.4  2328.1  1117.5 2328.47  1137.5 2331.34  1157.4 2341.84
  1317.1 2406.41    1367  2429.9  1386.9 2441.92  1466.8 2471.04  1486.7 2482.36
  1566.6 2512.56  1586.5 2521.78  1756.1 2559.83    1796 2556.66  1875.9 2538.46
  1905.8 2528.95  1925.8 2518.21  2005.6  2488.7  2025.5 2477.47  2115.3 2449.95
#Mann= 3 , 0 , 0
       0      .1       0   678.5    .045       0  1063.4      .1       0
Bank Sta=678.5,1063.4
XS Rating Curve= 0 ,0
Exp/Cntr=0.3,0.1

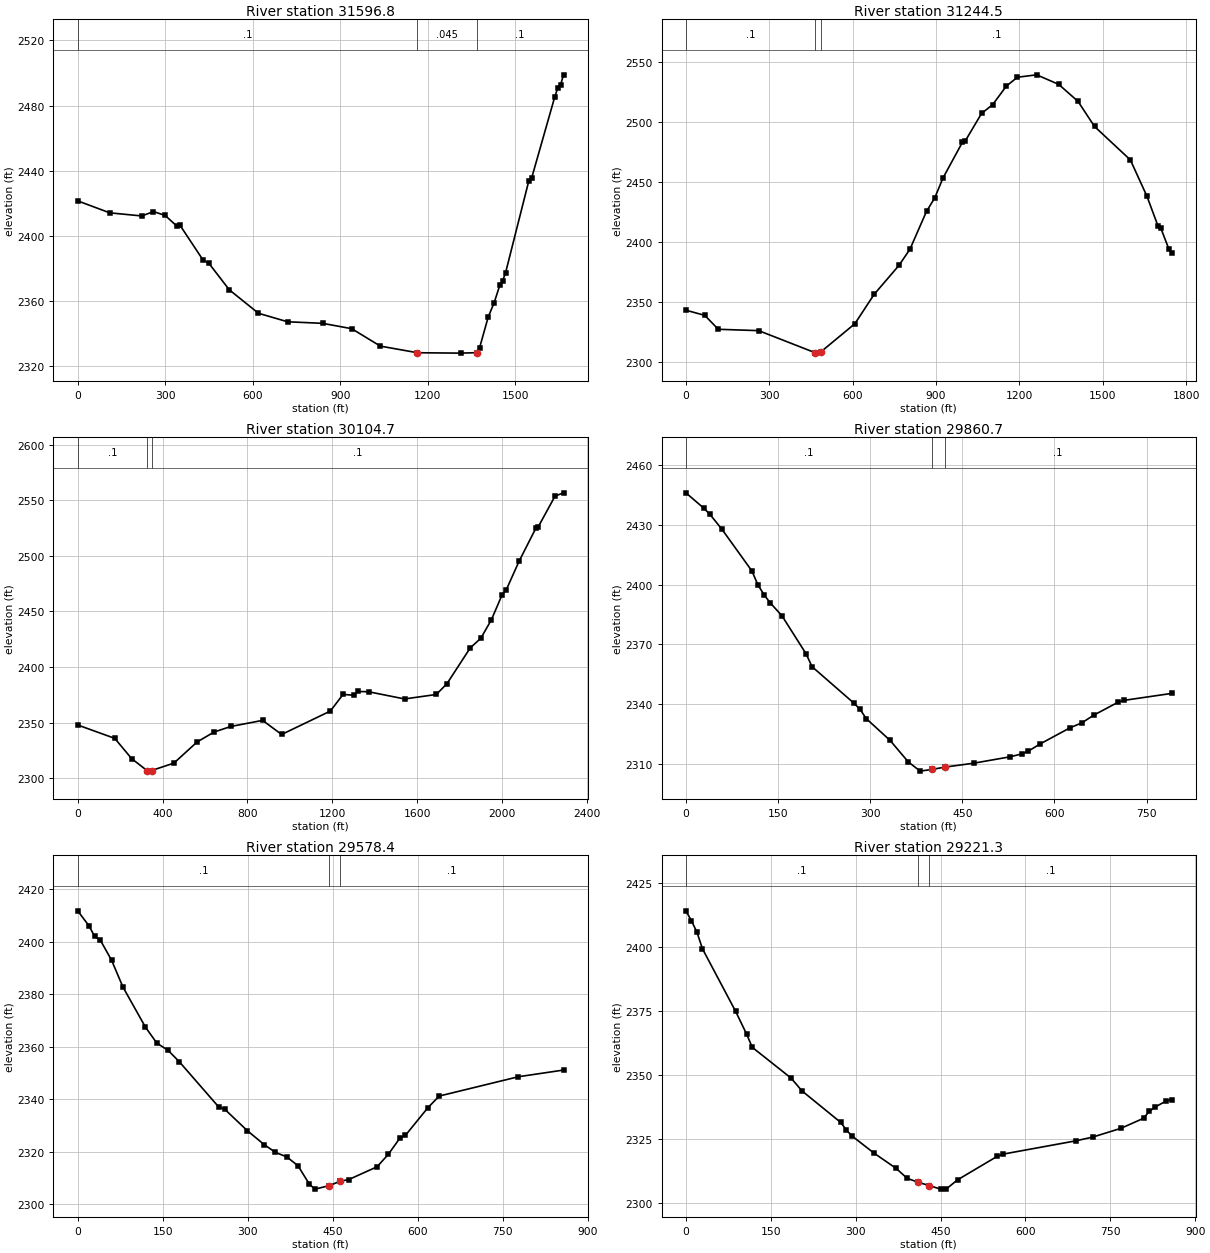
Type RM Length L Ch R = 1 ,31596.8 ,339.5,351.9,361.3
XS GIS Cut Line= 5
     1965289.764      149630.097     1965505.413      148705.884
     1965345.228      148369.879     1965347.934      148343.928
     1965228.684      148049.623
#Sta/Elev= 30
       0  2421.5   109.9 2414.15   219.8 2412.24   259.7 2414.94   299.7 2412.56
   339.7 2406.03   349.6 2406.79   429.6 2385.16   449.5 2383.18   519.5 2366.91
   619.4 2352.51   719.3 2347.28   839.2 2346.33     939 2343.04  1037.2 2332.34
  1164.5 2328.28  1312.1 2328.04  1367.2 2328.31  1377.1 2331.18  1406.9 2350.24
  1426.8 2358.81  1446.6 2369.68  1456.5 2372.48  1466.4 2377.41  1545.8 2433.65
  1555.8 2435.56  1635.1 2485.45  1645.1 2490.66    1655  2492.8  1664.9 2498.87
#Mann= 3 , 0 , 0
       0      .1       0  1164.5    .045       0  1367.2      .1       0
Bank Sta=1164.5,1367.2
XS Rating Curve= 0 ,0
Exp/Cntr=0.3,0.1

Type RM Length L Ch R = 1 ,31244.5 ,1104.6,1138.3,1172
XS GIS Cut Line= 4
     1965547.423       148731.09     1965667.851      148434.221
     1965683.398      148047.785     1966050.317      147073.984
#Sta/Elev= 30
       0 2342.88      68 2338.56   116.5 2326.95   262.1 2325.81   466.3 2307.29
   469.1 2307.06   486.3 2308.24     608  2331.6   677.4 2356.12   766.6 2380.24
   806.2 2393.78   865.7 2425.31   895.4 2436.59   925.2 2453.25   994.5  2482.8
  1004.4 2483.78  1063.9 2507.06  1103.6 2514.31  1153.1 2529.86  1192.7 2537.21
  1262.1 2539.23  1341.4 2531.26  1410.8 2517.08  1470.2 2496.13  1599.1 2468.26
  1658.6 2438.06  1698.2 2413.36  1708.1 2411.68  1737.8 2393.82  1747.8 2390.63
#Mann= 3 , 0 , 0
       0      .1       0   466.3    .045       0   486.3      .1       0
Bank Sta=466.3,486.3
XS Rating Curve= 0 ,0
Exp/Cntr=0.3,0.1

Type RM Length L Ch R = 1 ,30104.7 ,249.3,243.9,240
XS GIS Cut Line= 4
     1965550.224      148932.736     1965673.452      148913.132
     1966496.599      148766.141     1967487.625      147881.397
#Sta/Elev= 30
       0 2347.77   174.6 2335.75   254.2 2317.52   328.2 2306.55   333.8 2306.27
   348.2 2306.82   453.3 2313.48   562.8 2332.51   642.4 2341.42     722 2346.46
   871.4 2351.93     961 2339.23  1190.7 2360.32  1250.6  2375.3  1300.6 2374.53
  1320.5 2377.92  1370.5 2377.69  1540.3  2371.2  1690.1 2375.22  1740.1 2384.92
  1849.9 2417.14  1899.9 2425.83  1949.8 2442.53  1999.8  2464.8  2019.8 2469.42
  2079.7 2494.96  2159.6    2525  2169.6 2525.79  2249.5 2553.68  2289.4 2556.64
#Mann= 3 , 0 , 0
       0      .1       0   328.2    .045       0   348.2      .1       0
Bank Sta=328.2,348.2
XS Rating Curve= 0 ,0
Exp/Cntr=0.3,0.1

Type RM Length L Ch R = 1 ,29860.7 ,299.2,282.3,264
XS GIS Cut Line= 3
     1965570.805      149262.932     1965947.124      149097.972
     1966302.197      148962.143
#Sta/Elev= 30
       0 2446.07    29.4  2438.3    39.1 2435.27    58.7 2427.78   107.6 2406.79
   117.4 2399.76   127.2 2394.96     137 2390.94   156.5  2384.3   195.7 2365.23
   205.4 2358.79   273.9 2340.37   283.7 2337.32   293.5 2332.75   332.6 2321.72
     362    2311   381.5 2306.33   401.1  2307.2   421.1 2308.32   469.4 2310.35
   527.9 2313.52   547.4 2315.02   557.1 2316.28   576.6 2319.95   625.3 2328.06
   644.8 2330.59   664.3 2334.46   703.3 2340.86   713.1 2341.85     791 2345.35
#Mann= 3 , 0 , 0
       0      .1       0   401.1    .045       0   421.1      .1       0
Bank Sta=401.1,421.1
XS Rating Curve= 0 ,0
Exp/Cntr=0.3,0.1

Type RM Length L Ch R = 1 ,29578.4 ,341.2,355.6,371.7
XS GIS Cut Line= 2
     1965981.056      149615.627     1966395.552      148865.054
#Sta/Elev= 30
       0 2411.81    19.9 2406.09    29.9 2402.05    39.9 2400.65    59.8 2392.97
    79.8 2382.77   119.6 2367.45   139.6  2361.4   159.5 2358.63   179.5 2354.24
   249.2 2336.95   259.2 2336.23   299.1 2328.05     329 2322.71     349 2319.72
   368.9 2318.02   388.8 2314.63   408.8 2307.63   418.7 2305.72   443.6 2307.04
   463.6 2308.74   478.6 2309.39   528.4 2314.24   548.4 2319.04   568.3 2325.06
   578.3 2326.19   618.1 2336.77   638.1  2341.2   777.7 2348.56   857.4 2351.11
#Mann= 3 , 0 , 0
       0      .1       0   443.6    .045       0   463.6      .1       0
Bank Sta=443.6,463.6
XS Rating Curve= 0 ,0
Exp/Cntr=0.3,0.1

Type RM Length L Ch R = 1 ,29221.3 ,414.1,401.2,388.4
XS GIS Cut Line= 3
     1965992.992      149626.829     1966382.128      149467.849
     1966795.271      149321.961
#Sta/Elev= 30
       0    2414     9.8 2410.14    19.6 2405.65    29.3  2399.2      88 2374.79
   107.5 2365.87   117.3 2360.81   185.7 2348.86   205.3 2343.81   273.7 2331.54
   283.5 2328.61   293.3 2326.31   332.4  2319.6   371.5 2313.65     391 2309.78
   410.4 2308.24   430.4 2306.92   450.2 2305.56   460.2 2305.62   480.1 2309.18
   549.8 2318.29   559.8 2319.17   689.2 2324.38   719.1 2325.85   768.9 2329.26
   808.7 2333.16   818.7 2335.82   828.6 2337.47   848.6 2339.89   858.5 2340.44
#Mann= 3 , 0 , 0
       0      .1       0   410.4    .045       0   430.4      .1       0
Bank Sta=410.4,430.4
XS Rating Curve= 0 ,0
Exp/Cntr=0.3,0.1

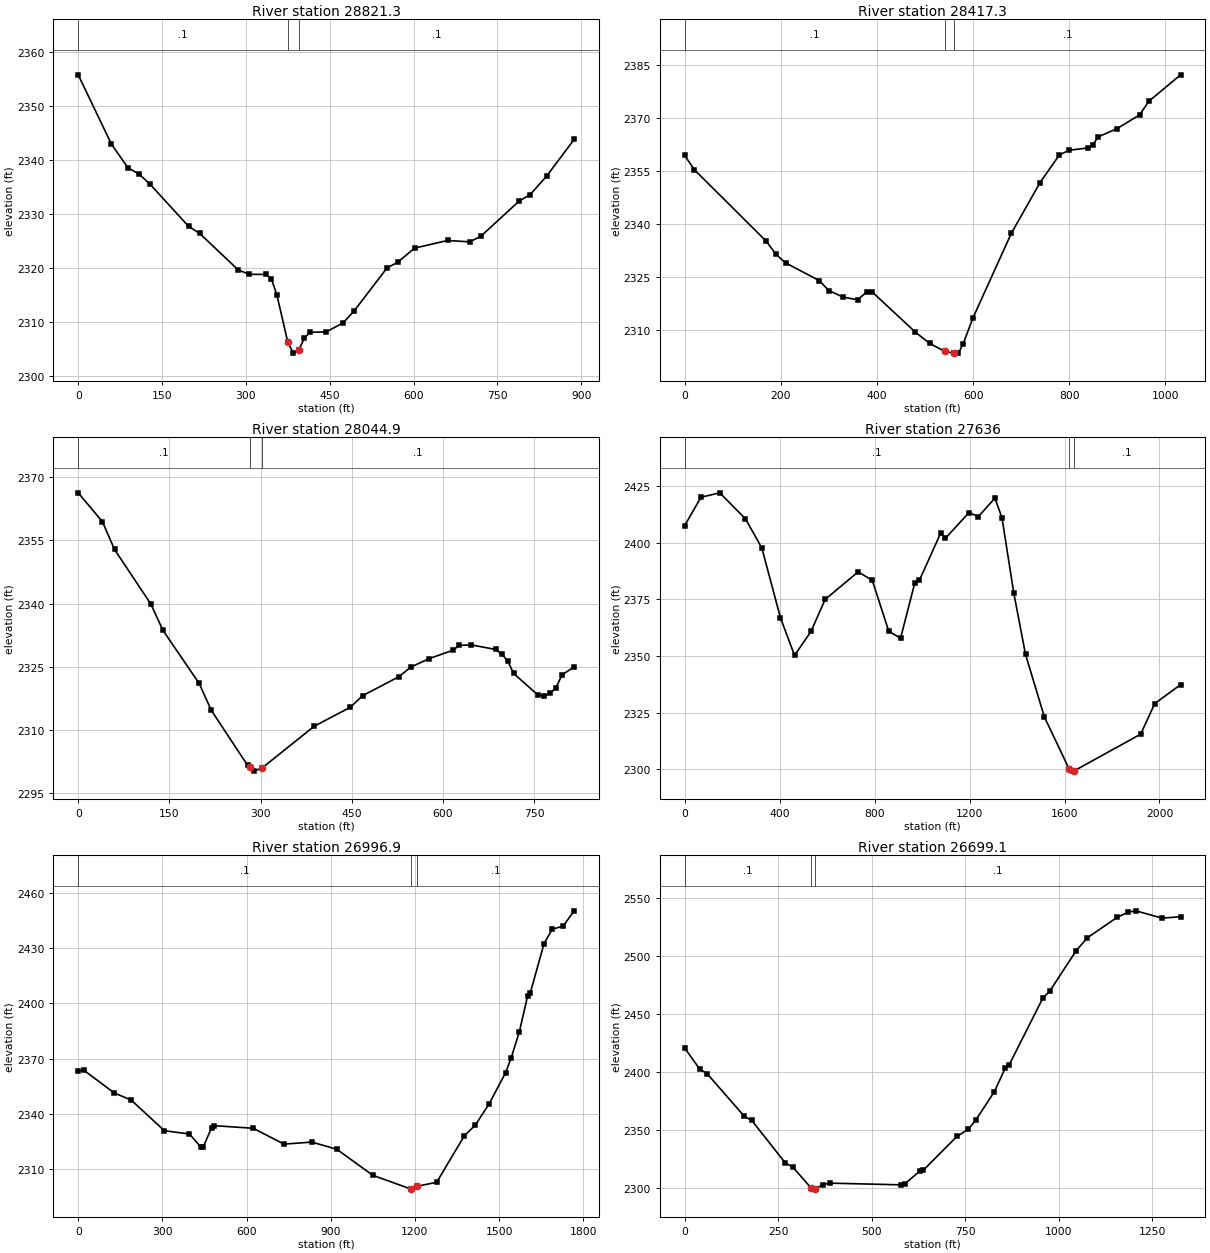
Type RM Length L Ch R = 1 ,28821.3 ,392.4,403.7,413.1
XS GIS Cut Line= 3
     1966349.057      150141.289     1966560.986      149808.119
     1966855.157      149413.192
#Sta/Elev= 30
       0 2355.83    59.2 2343.04    88.8 2338.63   108.6 2337.46   128.3  2335.6
   197.4 2327.77   217.2 2326.47   286.3  2319.7     306 2318.89   335.6 2318.86
   345.5 2318.08   355.4 2315.08   375.1 2306.26   384.9 2304.29   394.9 2304.94
   404.7 2307.08   414.6 2308.14   444.1 2308.24   473.6 2309.87   493.4 2312.07
   552.4 2320.05   572.1 2321.16   601.7 2323.73   660.8 2325.15   700.2  2324.9
   719.9 2325.89   788.8 2332.44   808.5 2333.64   838.1 2337.08   887.3 2343.87
#Mann= 3 , 0 , 0
       0      .1       0   375.1    .045       0   394.9      .1       0
Bank Sta=375.1,394.9
XS Rating Curve= 0 ,0
Exp/Cntr=0.3,0.1

Type RM Length L Ch R = 1 ,28417.3 ,359.3,372.3,385.3
XS GIS Cut Line= 3
     1966425.422      150203.081     1967202.137      149750.057
     1967325.365      149701.513
#Sta/Elev= 30
       0 2359.41      20  2355.4   169.8 2335.14   189.8 2331.46   209.8 2329.04
   279.7 2324.04   299.7 2321.22   329.7 2319.35   359.7  2318.6   379.6  2320.9
   389.6 2320.87   479.6 2309.47   509.5 2306.27   540.7 2304.01   559.5 2303.51
   560.7 2303.51   569.5 2303.51   579.5 2306.21   599.4  2313.4   679.4 2337.37
   739.3 2351.76   779.3 2359.54   799.3 2360.88   839.2 2361.53   849.2 2362.36
   859.2 2364.62   899.2 2366.99   946.5  2370.9   965.4 2374.73  1031.6 2382.21
#Mann= 3 , 0 , 0
       0      .1       0   540.7    .045       0   560.7      .1       0
Bank Sta=540.7,560.7
XS Rating Curve= 0 ,0
Exp/Cntr=0.3,0.1

Type RM Length L Ch R = 1 ,28044.9 ,419,408.7,398.3
XS GIS Cut Line= 2
     1966544.919      150287.781     1967358.973      150235.503
#Sta/Elev= 30
       0 2366.32    39.8 2359.47    59.7 2352.86   119.4 2339.89   139.3 2333.64
     199    2321   218.8 2314.64   278.5 2301.55   282.2 2301.04   288.5 2300.16
   302.2 2300.88     388 2310.82   447.7 2315.35   467.6 2318.08   527.2 2322.59
   547.1 2324.89     577  2326.9   616.8 2328.92   626.7 2330.06   646.6 2330.16
   686.4 2329.09   696.4 2328.01   706.3 2326.37   716.2 2323.38     756 2318.27
     766 2318.02   775.9 2318.63   785.9    2320   795.8 2323.08   815.7 2324.92
#Mann= 3 , 0 , 0
       0      .1       0   282.2    .045       0   302.2      .1       0
Bank Sta=282.2,302.2
XS Rating Curve= 0 ,0
Exp/Cntr=0.3,0.1

Type RM Length L Ch R = 1 ,27636   ,634.1,638.6,643.1
XS GIS Cut Line= 4
      1966021.73      151938.545     1966246.389      151500.571
      1966779.75      150746.267     1967377.644      150437.149
#Sta/Elev= 30
       0  2407.5    68.9 2419.96   147.7 2421.91     256 2410.46   324.9 2397.62
   403.6 2366.78   462.7  2350.2     532 2360.76   591.6 2374.88   730.6 2387.05
   790.2 2383.32   859.8 2360.83   909.4 2357.79     969 2382.06   988.9 2383.36
  1078.3 2404.15  1098.2 2401.85  1197.5 2413.17  1237.2 2411.43  1306.8 2419.58
  1336.6  2410.9  1386.2 2377.76  1435.8 2350.65    1515 2323.13  1619.1 2300.19
  1633.8 2299.18  1639.1 2299.21  1920.9 2315.49  1980.2 2328.99  2089.1 2337.32
#Mann= 3 , 0 , 0
       0      .1       0  1619.1    .045       0  1639.1      .1       0
Bank Sta=1619.1,1639.1
XS Rating Curve= 0 ,0
Exp/Cntr=0.3,0.1

Type RM Length L Ch R = 1 ,26996.9 ,312.9,296.8,280.8
XS GIS Cut Line= 4
     1966481.438      151871.079     1967046.146      151167.987
     1967527.012      151015.949     1967641.731      150672.947
#Sta/Elev= 30
       0 2363.24    19.8 2363.79   128.8 2351.36   188.3 2347.63   307.2 2330.91
   396.4 2329.14     436 2322.23   445.9 2322.19   475.7 2332.61   485.6 2333.65
   624.3 2332.22   733.3 2323.62   832.4 2324.74   921.6 2320.85  1050.1  2306.7
  1186.8 2299.19  1206.8 2300.73  1277.6 2302.89  1376.5 2328.17  1415.9 2334.04
  1464.8 2345.53  1523.4  2362.4    1543 2370.33  1572.3 2384.55  1601.6 2403.92
  1611.4 2405.68  1660.3 2432.47  1689.6 2440.29  1728.7 2442.06  1767.8 2450.32
#Mann= 3 , 0 , 0
       0      .1       0  1186.8    .045       0  1206.8      .1       0
Bank Sta=1186.8,1206.8
XS Rating Curve= 0 ,0
Exp/Cntr=0.3,0.1

Type RM Length L Ch R = 1 ,26699.1 ,386.4,391.2,396.1
XS GIS Cut Line= 2
     1967200.638      151626.907     1967944.703      150530.136
#Sta/Elev= 30
       0 2420.87    39.9 2402.72    59.8 2398.77   159.4 2361.96   179.4  2358.4
     269 2321.75     289 2318.22   338.8 2299.88   348.8 2299.24   368.7 2303.09
   388.6 2304.39     578 2302.94   587.9 2303.67   627.8 2314.63   637.8 2315.54
   727.4 2344.64   757.3 2350.66   777.3 2358.46   827.1  2382.9     857 2403.71
     867 2406.19   956.6 2463.47   976.6 2470.29  1046.3 2504.71  1076.2 2515.81
  1155.9 2533.41  1185.8 2537.88  1205.8    2539  1275.5 2532.72  1325.3 2533.89
#Mann= 3 , 0 , 0
       0      .1       0   338.8    .045       0   348.8      .1       0
Bank Sta=338.8,348.8
XS Rating Curve= 0 ,0
Exp/Cntr=0.3,0.1

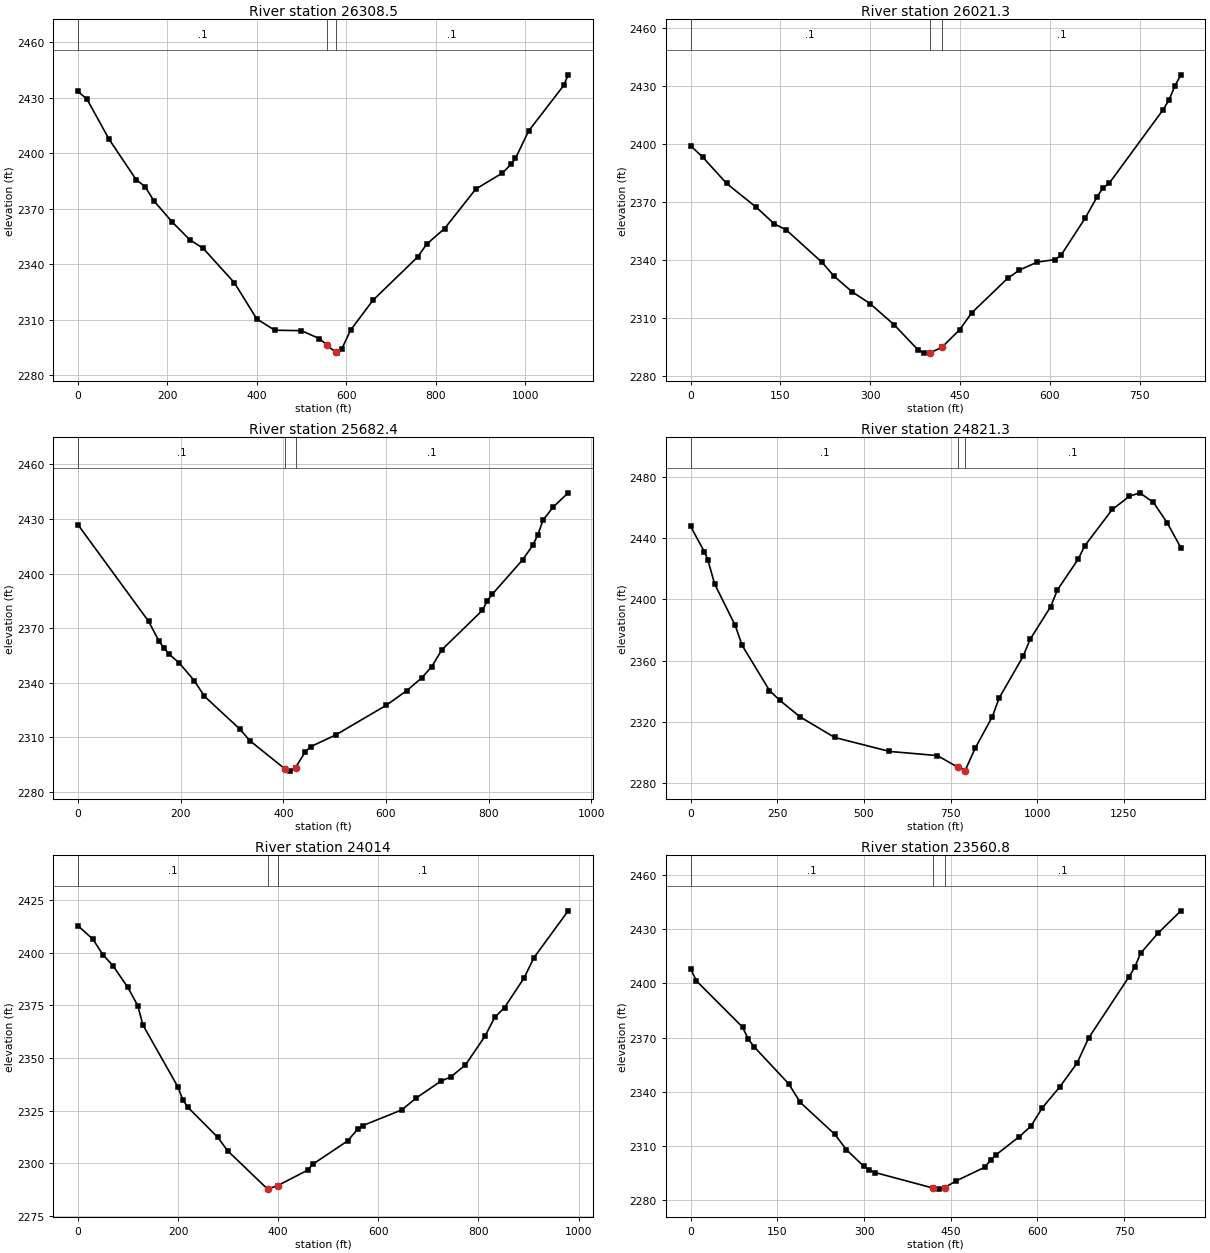
Type RM Length L Ch R = 1 ,26308.5 ,286.6,287.2,287.8
XS GIS Cut Line= 3
     1967377.644      151770.256     1968008.723      151142.911
     1968165.559       151008.48
#Sta/Elev= 30
       0 2433.31      20 2429.24      70  2407.4     130 2385.76     150 2381.97
     170 2374.24     210 2363.03     250 2353.26     280 2348.62   349.9 2330.02
   399.9 2310.51   439.9  2304.4   499.9 2304.13   539.9 2299.87   556.6 2296.47
   576.6 2292.38   579.9 2292.01   589.9 2294.17   609.9  2304.5   659.9 2320.59
   759.9 2343.98   779.9 2350.87   819.9 2359.26   889.8 2380.64   948.9 2389.21
   968.5 2393.96   978.4 2397.14  1007.9 2411.98  1086.6 2436.64  1096.4 2442.31
#Mann= 3 , 0 , 0
       0      .1       0   556.6    .045       0   576.6      .1       0
Bank Sta=556.6,576.6
XS Rating Curve= 0 ,0
Exp/Cntr=0.3,0.1

Type RM Length L Ch R = 1 ,26021.3 ,331.1,338.8,346.6
XS GIS Cut Line= 3
     1967669.598      151868.915     1967967.383      151587.818
     1968264.331       151305.84
#Sta/Elev= 30
       0 2399.08      20  2393.3    59.9 2379.64   109.9 2367.16   139.8 2358.61
   159.8 2355.49   219.7 2338.61   239.7 2331.46   269.7 2323.42   299.6  2317.3
   339.6 2306.43   379.5 2293.38   389.5 2291.61   399.5 2291.72   419.5 2294.58
   449.4 2303.74   469.4 2312.44   529.4 2330.35   549.3 2334.69   579.3 2338.83
   609.3 2340.13   619.2 2342.56   659.2 2361.66   679.2 2372.75   689.2 2377.38
   699.2 2379.68     789 2417.69     799 2422.78     809 2430.17     819  2435.9
#Mann= 3 , 0 , 0
       0      .1       0   399.5    .045       0   419.5      .1       0
Bank Sta=399.5,419.5
XS Rating Curve= 0 ,0
Exp/Cntr=0.3,0.1

Type RM Length L Ch R = 1 ,25682.4 ,850.1,861.1,872
XS GIS Cut Line= 3
     1967792.379      152034.902     1968236.508      151822.534
     1968632.333      151583.546
#Sta/Elev= 30
       0  2426.8   137.8 2373.66   157.5    2363   167.4  2359.2   177.2  2355.8
   196.9 2350.98   226.4 2341.22   246.2 2332.63   315.1 2314.61   334.8 2308.21
   403.7 2292.55   413.5 2291.48   423.7 2293.45   443.1 2302.24   452.9 2304.86
   502.1 2311.37   600.5 2327.65   639.9 2335.57   669.4 2342.66     689 2348.84
   708.7 2358.12   787.4  2379.7   797.3 2385.08   807.1 2388.67   866.1 2407.56
   885.8 2415.53   895.6 2421.22   905.5 2429.21   925.2 2436.41   954.7  2444.3
#Mann= 3 , 0 , 0
       0      .1       0   403.7    .045       0   423.7      .1       0
Bank Sta=403.7,423.7
XS Rating Curve= 0 ,0
Exp/Cntr=0.3,0.1

Type RM Length L Ch R = 1 ,24821.3 ,812.5,806.8,801.2
XS GIS Cut Line= 3
     1967946.223      152293.878     1968727.502      152282.169
       1969360.5      152270.637
#Sta/Elev= 30
       0 2447.55    39.6 2431.02    49.4 2425.88    69.2 2409.98   128.6 2382.92
   148.4 2369.99   227.5 2340.45   257.2 2334.02   316.5 2323.14   415.4 2309.83
   573.7  2300.7   712.1 2297.99   771.4 2290.31   791.3 2287.84   791.4 2287.88
   820.9  2302.8   870.4 2323.32   890.2 2335.61   959.4 2362.82   979.2 2373.76
  1038.6 2395.12  1058.4 2406.18  1117.7 2426.01  1137.5 2435.02  1216.6 2458.63
  1266.1 2467.23  1295.8 2469.47  1335.3 2463.22  1374.9 2449.92  1414.5 2433.58
#Mann= 3 , 0 , 0
       0      .1       0   771.4    .045       0   791.4      .1       0
Bank Sta=771.4,791.4
XS Rating Curve= 0 ,0
Exp/Cntr=0.3,0.1

Type RM Length L Ch R = 1 ,24014   ,441.6,453.2,464.7
XS GIS Cut Line= 3
     1967884.269       152746.05     1968434.421      152602.981
     1968716.726      152901.417
#Sta/Elev= 30
       0 2412.84    29.9 2406.47    49.9 2399.06    69.8 2393.96    99.7 2383.54
   119.7 2374.82   129.6 2365.81   199.5 2336.41   209.4  2330.3   219.4 2326.71
   279.2 2312.41   299.2 2305.97   378.9  2287.8   398.9 2289.48   458.8 2296.79
   468.7 2299.55   538.5 2310.68   558.5 2316.16   568.4 2317.91   646.7  2325.4
     676 2331.13     725 2339.06   744.5 2341.05   773.8  2346.7     813  2360.4
   832.5 2369.35   852.1 2374.02   891.2 2388.12   910.8 2397.68   979.2 2419.93
#Mann= 3 , 0 , 0
       0      .1       0   378.9    .045       0   398.9      .1       0
Bank Sta=378.9,398.9
XS Rating Curve= 0 ,0
Exp/Cntr=0.3,0.1

Type RM Length L Ch R = 1 ,23560.8 ,346.5,339.4,331.5
XS GIS Cut Line= 2
     1967829.481      152995.071     1968659.001      153172.545
#Sta/Elev= 30
       0 2407.96      10 2401.32    89.8 2375.76    99.8  2369.1   109.8 2364.87
   169.7 2344.38   189.6 2334.12   249.5 2316.44   269.5 2307.97   299.4 2298.78
   309.4 2296.55   319.4 2295.28   419.7  2286.7   429.1 2286.13   439.7 2287.01
   459.1 2290.65     509 2298.25     519 2302.26   528.9 2305.23   568.8 2315.21
   588.8 2320.97   608.8 2331.24   638.7 2342.66   668.6 2355.85   688.6  2369.7
   758.5 2403.61   768.4 2408.87   778.4 2416.54   808.4 2427.65   848.3 2440.09
#Mann= 3 , 0 , 0
       0      .1       0   419.7    .045       0   439.7      .1       0
Bank Sta=419.7,439.7
XS Rating Curve= 0 ,0
Exp/Cntr=0.3,0.1

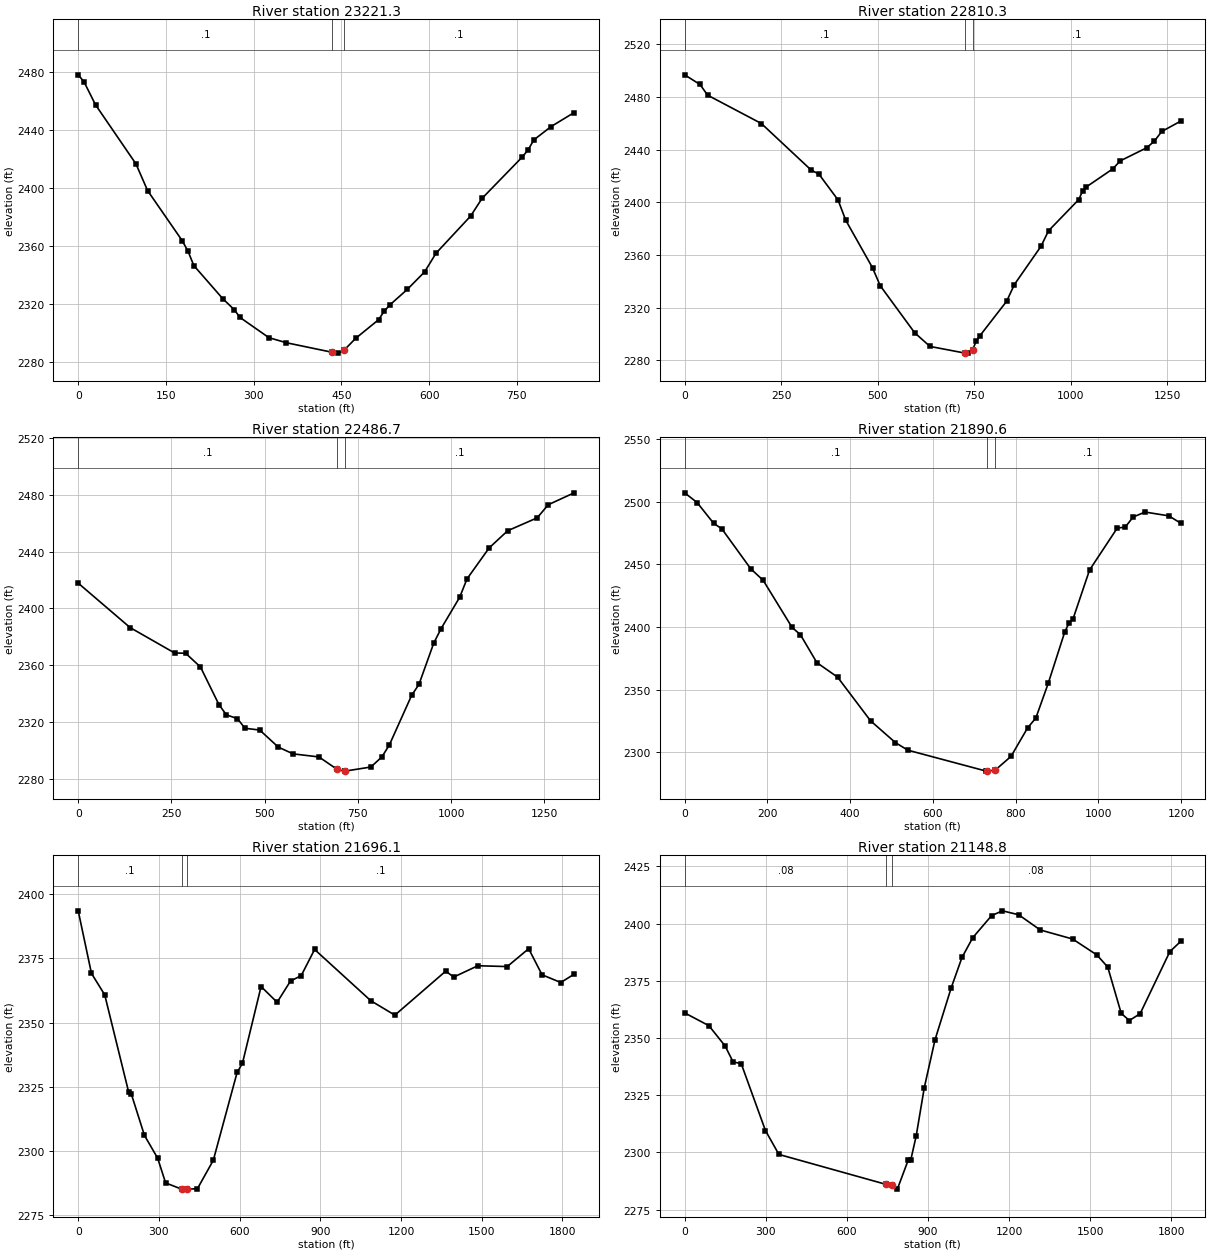
Type RM Length L Ch R = 1 ,23221.3 ,401.2,410.8,421.1
XS GIS Cut Line= 3
     1967814.601      153420.022     1968258.311      153389.959
     1968659.595      153350.436
#Sta/Elev= 30
       0 2477.92     9.9 2473.12    29.6 2457.27    98.8 2416.53   118.6 2398.22
   177.9 2363.65   187.8 2356.36   197.7 2346.55   247.1 2323.77   266.8 2316.17
   276.7 2310.81   326.1 2296.89   355.8 2293.41   434.7  2286.8   444.7 2286.25
   454.7 2288.31   474.2 2296.35   513.6 2309.27   523.4 2315.25   533.2 2319.56
   562.8 2330.18   592.2 2342.17   611.9  2355.1   670.9 2380.62   690.6 2392.86
   759.4 2421.37   769.3 2426.26   779.1 2433.12   808.6  2442.3     848 2451.94
#Mann= 3 , 0 , 0
       0      .1       0   434.7    .045       0   454.7      .1       0
Bank Sta=434.7,454.7
XS Rating Curve= 0 ,0
Exp/Cntr=0.3,0.1

Type RM Length L Ch R = 1 ,22810.3 ,346.9,323.3,299.7
XS GIS Cut Line= 3
     1967448.594      153558.934      1968299.99       153831.53
     1968637.118       153633.27
#Sta/Elev= 30
       0 2496.94    39.7 2489.59    59.6 2481.45   198.7 2459.93   327.8 2424.53
   347.7  2421.5   397.3 2401.88   417.2  2386.5   486.7  2350.3   506.6  2336.7
     596 2300.87   635.7 2290.49   726.4 2285.43     735 2285.41   746.4 2288.05
   754.9 2294.27   764.8 2298.54   834.4 2324.89   854.2 2337.48   923.3 2366.61
   942.9 2378.42  1021.1 2402.11  1030.9 2408.45  1040.6 2411.71  1109.1  2425.4
  1128.6 2431.53  1197.1 2441.48  1216.6 2446.39  1236.2 2453.88  1285.1  2461.7
#Mann= 3 , 0 , 0
       0      .1       0   726.4    .045       0   746.4      .1       0
Bank Sta=726.4,746.4
XS Rating Curve= 0 ,0
Exp/Cntr=0.3,0.1

Type RM Length L Ch R = 1 ,22486.7 ,617.6,595.7,573.4
XS GIS Cut Line= 3
     1967579.291      154496.216     1968296.256      153962.227
     1968657.835      153718.757
#Sta/Elev= 30
       0 2417.75   139.1 2386.46   258.3 2368.57   288.1 2368.34   327.8  2358.7
   377.4 2332.14   397.3 2324.96   427.1 2322.29     447 2315.51   486.7 2314.26
   536.4 2302.27   576.1 2297.47   645.6 2295.31   694.6 2286.49   714.6 2285.32
   715.2 2285.31   784.7  2288.2   814.5 2295.37   834.4 2303.79     894 2338.63
   913.8 2346.46   953.4 2375.51   973.2 2385.78  1022.8 2407.74  1042.6 2420.75
    1102 2442.58  1151.6 2454.66  1230.8 2463.76  1260.5    2473  1329.9 2481.38
#Mann= 3 , 0 , 0
       0      .1       0   694.6    .045       0   714.6      .1       0
Bank Sta=694.6,714.6
XS Rating Curve= 0 ,0
Exp/Cntr=0.3,0.1

Type RM Length L Ch R = 1 ,21890.6 ,186.2,194.4,203.1
XS GIS Cut Line= 3
      1968531.51      154884.572     1968561.383      153906.214
      1968723.94      153757.659
#Sta/Elev= 30
       0 2507.04      30 2499.31    69.9 2482.75    89.9 2478.27   159.8 2446.38
   189.8 2437.19   259.7 2399.58   279.7 2393.84   319.6 2371.49   369.6 2359.95
   449.5 2325.03   509.4 2307.69   539.4 2301.63   729.1  2284.9   730.6  2284.9
   750.6 2285.66     789 2296.68     829 2319.38     849 2327.29   878.9 2354.97
   918.9 2395.99   928.9 2402.97   938.9 2406.42   978.8  2445.4  1045.8 2478.92
    1065 2479.65  1084.1 2487.68  1112.9  2491.7  1170.3 2488.67    1199 2482.87
#Mann= 3 , 0 , 0
       0      .1       0   730.6    .045       0   750.6      .1       0
Bank Sta=730.6,750.6
XS Rating Curve= 0 ,0
Exp/Cntr=0.3,0.1

Type RM Length L Ch R = 1 ,21696.1 ,545.4,546.9,548.5
XS GIS Cut Line= 3
     1968568.852      154604.508      1968807.84      154010.771
     1969110.309      152845.703
#Sta/Elev= 30
       0 2393.55    49.2 2369.18    98.5 2360.82   187.1 2323.09   196.9 2322.35
   246.2 2306.05   295.4 2297.15   324.9 2287.53     384 2285.11   393.9  2285.1
   403.7  2285.1   443.1 2285.25   502.2 2296.34   590.8  2330.6   610.5 2334.12
   679.8 2364.05   739.5 2357.91   789.2 2366.19     829  2368.3   878.8 2378.49
  1087.7 2358.52  1177.2  2352.9  1366.2 2370.04  1396.1 2367.75  1485.6 2372.15
    1595 2371.83  1674.6 2378.79  1724.4 2368.62    1794 2365.62  1843.7 2368.86
#Mann= 3 , 0 , 0
       0      .1       0     384    .045       0   403.7      .1       0
Bank Sta=384,403.7
XS Rating Curve= 0 ,0
Exp/Cntr=0.3,0.1

Type RM Length L Ch R = 1 ,21148.8 ,321.8,326.7,331.7
XS GIS Cut Line= 3
     1968901.195      154899.509     1969311.956      154003.303
      1969431.45      153163.109
#Sta/Elev= 30
       0 2360.97    89.6 2355.38   149.4 2346.53   179.2 2339.52   209.1  2338.8
   298.7 2309.54   348.5 2299.08   745.8 2285.96   765.8  2285.8   786.7 2283.91
   826.5  2296.5   836.5 2296.76   856.4 2307.19   886.3 2328.28   926.1 2349.24
   985.9 2371.95  1025.8 2385.22  1065.7 2393.88  1135.6 2403.54  1175.6  2405.6
  1235.5 2403.88  1315.3 2397.23  1435.1 2393.27    1525 2386.29  1564.9 2381.01
  1614.8 2360.76  1644.8 2357.64  1684.7 2360.62  1794.6 2387.75  1834.5  2392.2
#Mann= 3 , 0 , 0
       0     .08       0   745.8    .045       0   765.8     .08       0
Bank Sta=745.8,765.8
XS Rating Curve= 0 ,0
Exp/Cntr=0.3,0.1