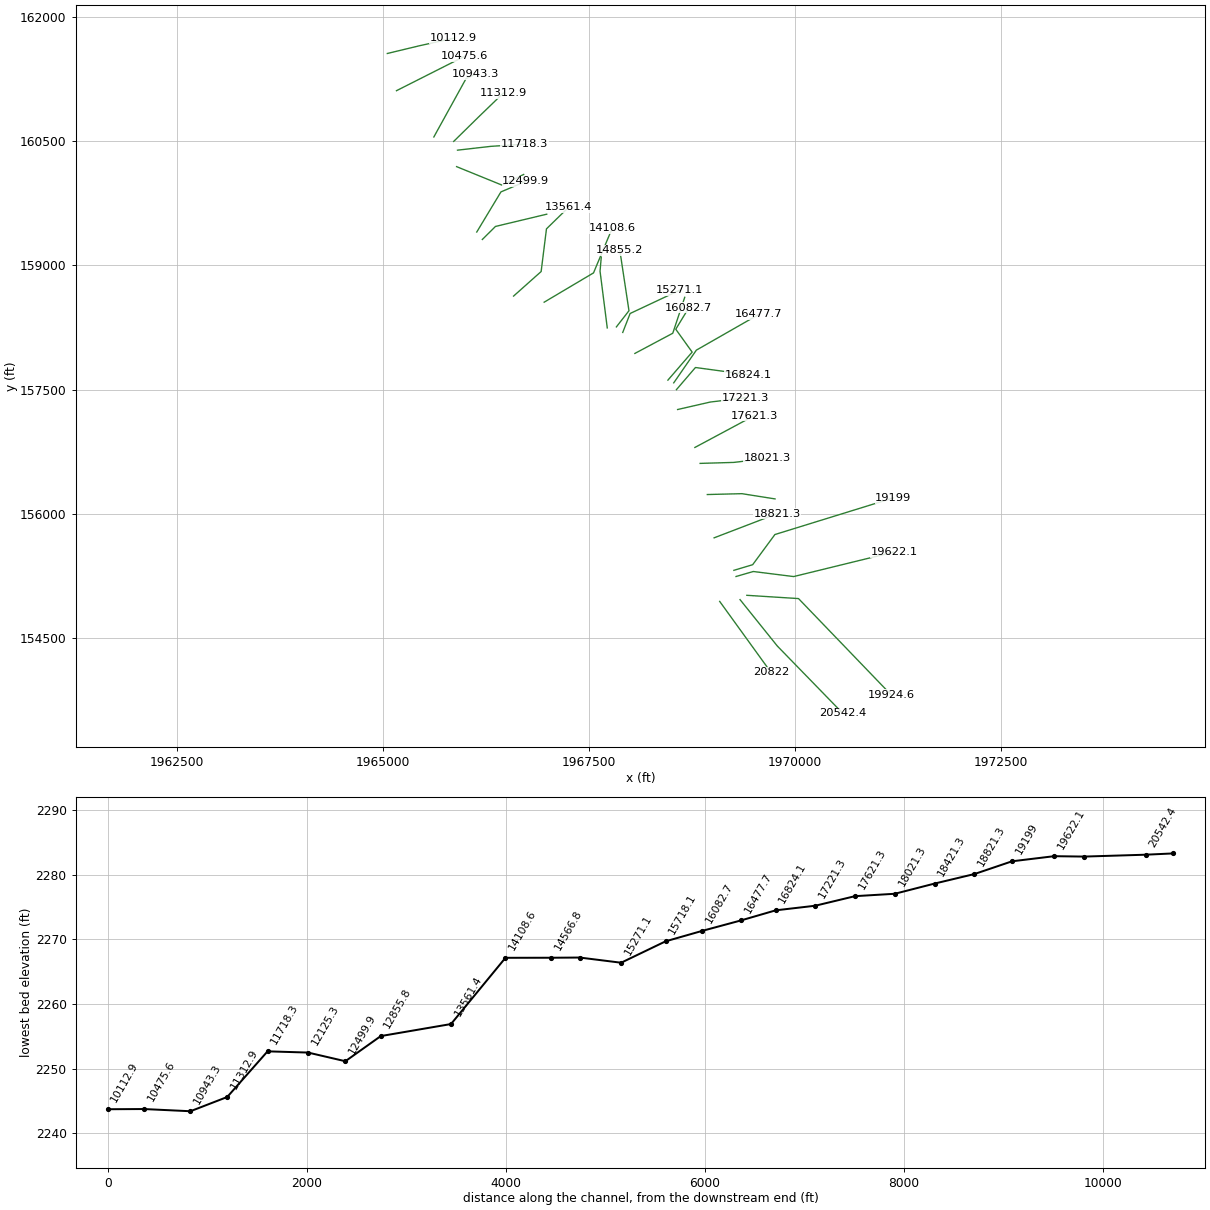
HEC-RAS study LrlCrk2.prj: LrlCrk2

--- LrlCrk2.g01 (geometry) --- (continued)

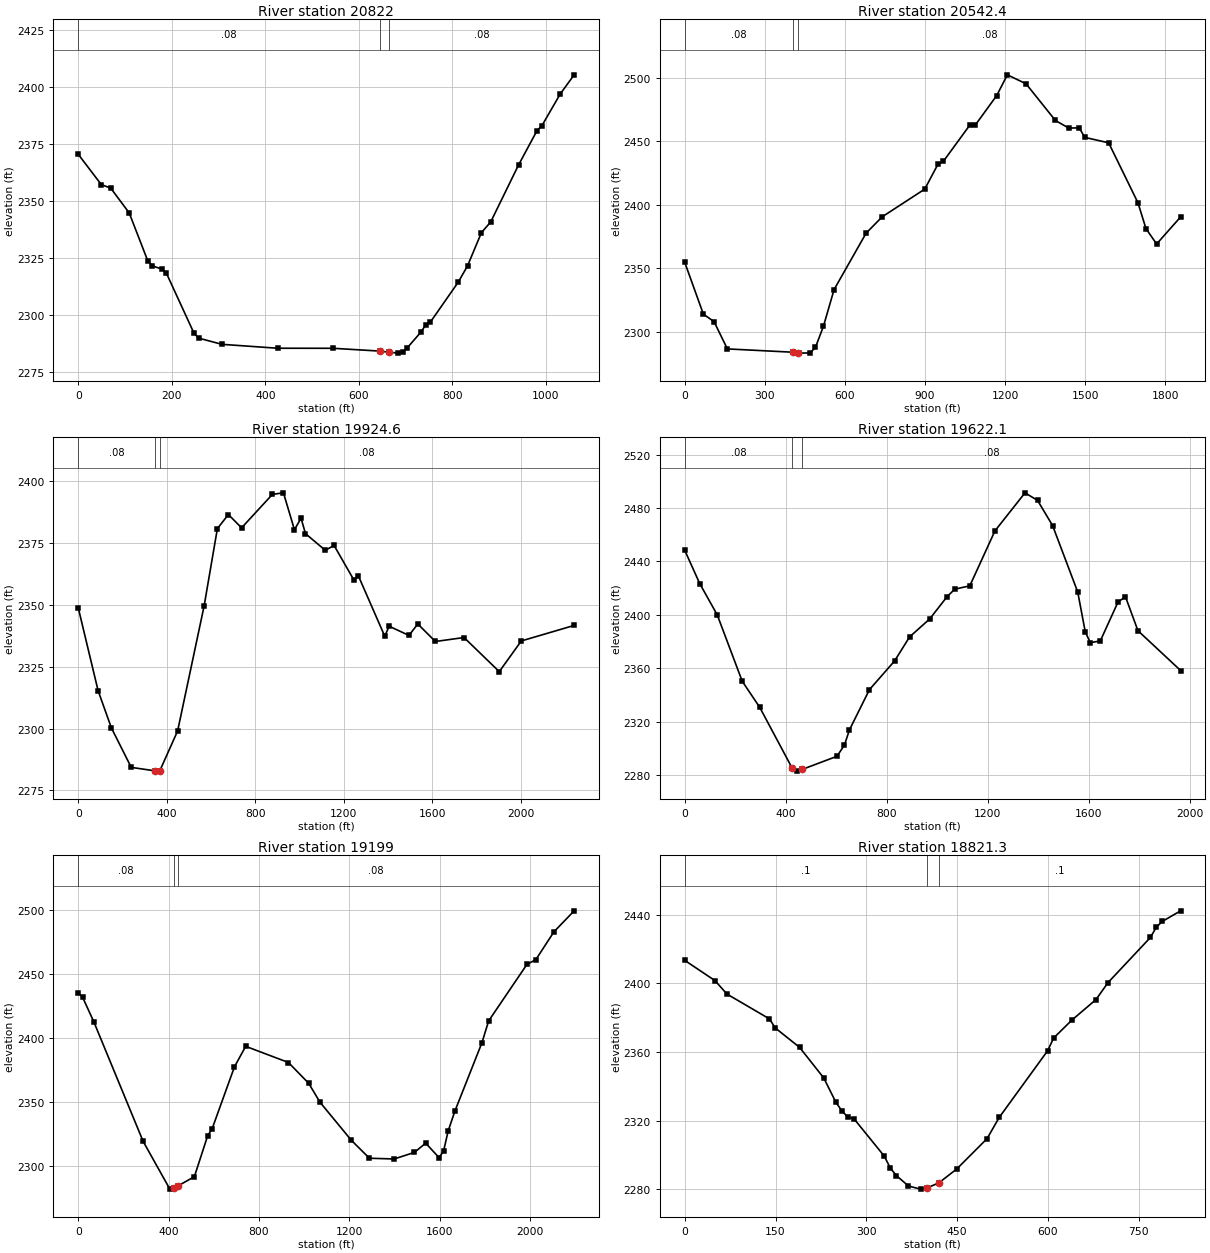
Type RM Length L Ch R = 1 ,20822   ,278.1,279.6,280.5
XS GIS Cut Line= 2
     1969087.374      154941.377      1969710.28      154083.483
#Sta/Elev= 30
       0 2370.58    49.5 2357.24    69.4 2355.75     109 2344.84   148.6 2323.86
   158.5 2321.61   178.4 2320.19   188.3 2318.48   247.7 2291.96   257.6 2289.88
   307.2 2287.16   426.1 2285.45     545 2285.42   644.9 2284.19   664.9 2283.69
   683.7  2283.3   693.6  2283.7   703.5 2285.64   733.2 2292.66   743.1 2295.79
     753 2296.96   812.5 2314.48   832.3 2321.62     862  2336.2   881.8 2340.87
   941.3 2365.87   980.9    2381   990.8 2382.96  1030.5 2397.06  1060.2 2405.45
#Mann= 3 , 0 , 0
       0     .08       0   644.9    .045       0   664.9     .08       0
Bank Sta=644.9,664.9
XS Rating Curve= 0 ,0
Exp/Cntr=0.3,0.1

Type RM Length L Ch R = 1 ,20542.4 ,597.7,616.2,531.4
XS GIS Cut Line= 3
     1969334.361       154962.99     1969786.198      154402.861
     1970581.581      153588.807
#Sta/Elev= 30
       0 2354.78      70 2313.82     110  2307.9   159.9 2286.43   404.8 2283.82
   424.8 2283.11   429.8  2283.1   469.8 2283.27   489.8 2287.59   519.8 2304.28
   559.7  2333.2   679.7 2377.65   739.6 2390.47   899.4 2412.35   949.3 2432.17
   969.2 2434.27  1069.1 2463.06    1089  2462.9  1168.9 2486.08  1208.8  2502.4
  1278.7 2495.34  1388.6 2466.45  1438.5 2460.47  1478.4 2460.59  1498.4 2453.11
  1588.2 2448.83    1698 2401.58    1728  2381.2  1767.9  2369.1  1857.8 2390.43
#Mann= 3 , 0 , 0
       0     .08       0   404.8    .045       0   424.8     .08       0
Bank Sta=404.8,424.8
XS Rating Curve= 0 ,0
Exp/Cntr=0.3,0.1

Type RM Length L Ch R = 1 ,19924.6 ,304.3,303,301.7
XS GIS Cut Line= 3
     1969416.513      155015.269     1970043.949      154975.633
     1971164.115      153816.593
#Sta/Elev= 30
       0 2348.82    89.8 2315.31   149.7  2300.3   239.5 2284.33   348.4  2282.9
   359.2 2282.81   368.4  2282.9   449.1 2299.03   568.8  2349.5   628.7 2380.73
   678.4 2386.44   738.1 2381.06   877.4 2394.58   927.2  2395.2   976.9  2380.3
  1006.8 2384.96  1026.7 2378.73  1116.2 2371.98    1156 2373.95  1245.6 2359.97
  1265.5 2361.72  1384.9 2337.29  1404.8 2341.33  1494.3 2337.61  1534.1 2342.24
  1613.7 2335.16  1743.1 2336.77  1902.3 2322.99  2001.8 2335.38  2240.6 2341.65
#Mann= 3 , 0 , 0
       0     .08       0   348.4    .045       0   368.4     .08       0
Bank Sta=348.4,368.4
XS Rating Curve= 0 ,0
Exp/Cntr=0.3,0.1

Type RM Length L Ch R = 1 ,19622.1 ,392.8,422.8,451.7
XS GIS Cut Line= 4
     1969285.436      155242.353     1969494.931      155302.802
     1969984.864       155241.62     1971201.457      155538.056
#Sta/Elev= 30
       0  2448.5    59.5 2423.46   128.8 2400.03   227.9 2350.23     297 2330.75
   425.4 2285.21   445.2 2282.87   464.9 2284.12   603.2 2294.01   632.8 2302.46
   652.5 2313.77   731.7 2343.96     831 2365.37   890.7 2383.46   970.2 2396.91
  1039.7 2413.74  1069.6 2419.24  1129.2 2421.74  1228.6  2462.9  1347.8 2491.45
  1397.5 2485.77  1457.1 2466.87  1556.5 2417.14  1586.3 2387.35  1606.2 2379.14
    1646 2380.46  1715.5 2409.38  1745.3 2413.73    1795 2388.12    1964 2358.27
#Mann= 3 , 0 , 0
       0     .08       0   425.4    .045       0   464.9     .08       0
Bank Sta=425.4,464.9
XS Rating Curve= 0 ,0
Exp/Cntr=0.3,0.1

Type RM Length L Ch R = 1 ,19199   ,391.9,377.6,363.3
XS GIS Cut Line= 4
      1969259.33      155316.968     1969487.463      155384.954
     1969757.167      155749.311     1971193.989       156191.54
#Sta/Elev= 30
       0 2435.33    19.8 2431.64    69.4 2412.47   287.3 2319.33   405.6 2282.08
   421.9 2283.22   441.9 2284.63     514 2291.79   573.1 2323.84   592.8 2329.24
   691.4 2377.48   741.1 2393.49   930.3 2380.87  1019.9 2364.66  1069.7 2349.94
  1209.1  2320.1  1288.7 2306.18  1398.2  2305.6  1487.8 2310.74  1537.6 2317.94
  1597.4 2306.57  1617.3 2312.14  1637.2 2327.48    1667 2342.99  1786.5 2396.24
  1816.4 2413.34  1985.6 2457.36  2025.4 2461.16  2105.1  2482.8  2194.7  2499.2
#Mann= 3 , 0 , 0
       0     .08       0   421.9    .045       0   441.9     .08       0
Bank Sta=421.9,441.9
XS Rating Curve= 0 ,0
Exp/Cntr=0.3,0.1

Type RM Length L Ch R = 1 ,18821.3 ,408,399.5,386.7
XS GIS Cut Line= 3
     1969019.711      155709.643     1969402.284      155855.686
     1969784.857      156001.728
#Sta/Elev= 30
       0 2413.47    49.9 2401.68    69.9  2393.8   139.8 2379.38   149.8    2374
   189.8 2362.73   229.7  2344.9   249.7 2330.73   259.7 2325.69   269.7 2322.02
   279.7 2321.08   329.6 2299.34   339.6 2292.39   349.6    2288   369.6 2281.92
   389.5 2280.11   399.5 2280.72   419.5  2283.7   449.4 2291.88   499.4 2309.56
   519.4  2321.9   599.3 2360.72   609.3 2368.19   639.2 2378.56   679.2  2390.6
   699.2 2400.52   769.1  2426.8     779 2432.87     789 2436.21     819 2442.33
#Mann= 3 , 0 , 0
       0      .1       0   399.5    .045       0   419.5      .1       0
Bank Sta=399.5,419.5
XS Rating Curve= 0 ,0
Exp/Cntr=0.3,0.1

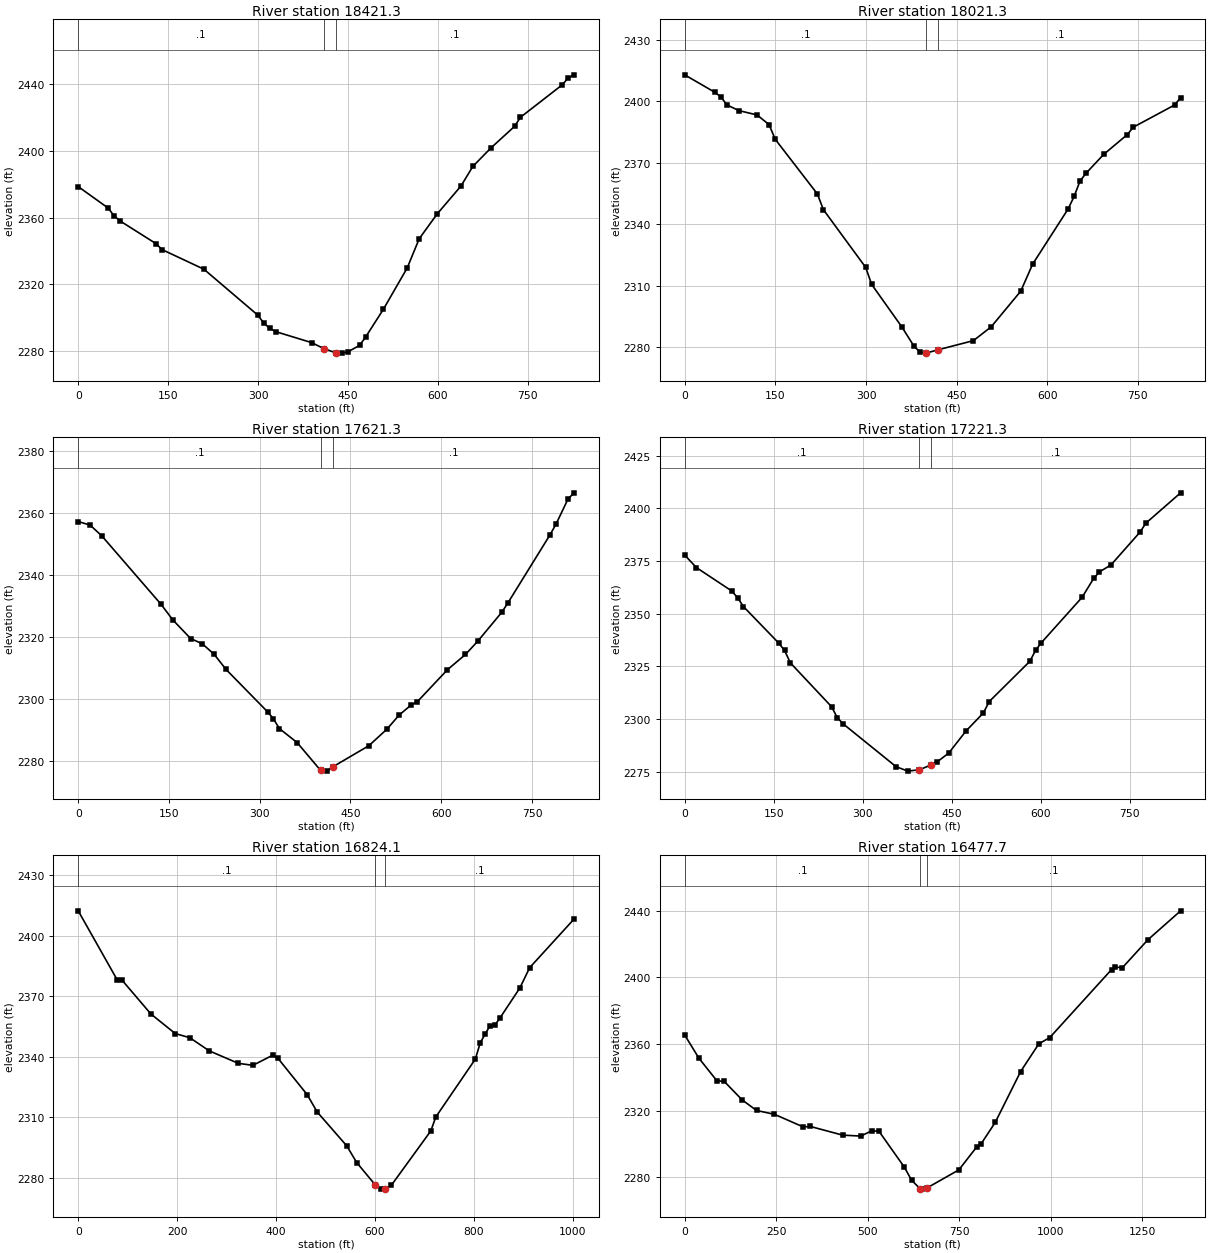
Type RM Length L Ch R = 1 ,18421.3 ,400.1,400.2,406.8
XS GIS Cut Line= 3
     1968937.166      156232.667     1969356.523      156243.119
     1969759.293      156179.735
#Sta/Elev= 30
       0 2378.66    49.9 2365.78    59.9 2361.07    69.9 2358.01   129.8 2344.38
   139.8 2340.83   209.7 2329.03   299.6 2301.43   309.6 2296.62   319.6 2293.53
   329.6 2291.53   389.5 2284.93   409.5 2281.38   429.5 2278.84   439.4 2278.64
   449.3 2279.33   469.2 2283.26   479.2 2288.21     509 2304.96   548.8 2329.84
   568.7 2347.31   598.5 2362.14   638.3 2378.95   658.2 2390.77     688 2401.74
   727.8 2414.84   737.7 2420.31   807.3 2439.77   817.3  2443.9   827.2 2445.79
#Mann= 3 , 0 , 0
       0      .1       0   409.5    .045       0   429.5      .1       0
Bank Sta=409.5,429.5
XS Rating Curve= 0 ,0
Exp/Cntr=0.3,0.1

Type RM Length L Ch R = 1 ,18021.3 ,388.2,399.8,409.2
XS GIS Cut Line= 3
     1968850.035      156608.958     1969259.019      156620.787
      1969667.64      156668.964
#Sta/Elev= 30
       0 2412.83    49.9 2404.31    59.9 2402.07    69.9 2398.15    89.8 2395.37
   119.8 2393.25   139.7 2388.52   149.7 2381.43   219.6  2354.7   229.5 2347.05
   299.4 2318.92   309.4 2310.57   359.3 2289.85   379.2 2280.56   389.2 2277.54
   399.2 2277.06   419.2 2278.68   477.7 2283.15   507.1 2289.87   556.1  2307.3
   575.7 2320.45   634.5 2347.41   644.3 2353.49   654.1 2360.98   663.9 2364.76
   693.2 2373.98   732.4 2383.68   742.2 2387.27   810.8 2398.14   820.6 2401.71
#Mann= 3 , 0 , 0
       0      .1       0   399.2    .045       0   419.2      .1       0
Bank Sta=399.2,419.2
XS Rating Curve= 0 ,0
Exp/Cntr=0.3,0.1

Type RM Length L Ch R = 1 ,17621.3 ,406.5,399.9,390.5
XS GIS Cut Line= 3
     1968786.043      156801.325     1969148.482      156994.347
      1969509.26      157187.187
#Sta/Elev= 30
       0 2357.33    19.6  2356.2    39.1 2352.69   136.9  2330.6   156.4 2325.55
   185.8 2319.54   205.3 2317.82   224.9 2314.38   244.4 2309.54   312.9 2295.87
   322.6 2293.63   332.4 2290.46   361.8 2285.92   400.6 2276.93   410.6 2276.69
   420.6 2278.05   480.5 2284.92   510.4 2290.28   530.4  2294.8   550.3 2298.07
   560.3 2299.08   610.2 2309.45   640.1 2314.39   660.1 2318.62     700    2328
     710 2330.98   779.8 2353.05   789.8 2356.53   809.7 2364.69   819.7 2366.62
#Mann= 3 , 0 , 0
       0      .1       0   400.6    .045       0   420.6      .1       0
Bank Sta=400.6,420.6
XS Rating Curve= 0 ,0
Exp/Cntr=0.3,0.1

Type RM Length L Ch R = 1 ,17221.3 ,406.4,397.1,390.2
XS GIS Cut Line= 3
     1968576.798      157259.694     1968972.464      157350.023
     1969399.618       157401.17
#Sta/Elev= 30
       0 2377.86    19.8 2371.91    79.2 2360.82    89.1 2357.65      99  2353.4
   158.4 2336.09   168.3 2332.57   178.2 2326.63   247.5 2305.85   257.4 2300.57
   267.3 2297.62   356.4 2277.32   376.2 2275.21   395.8 2275.87   415.8 2278.21
   425.4 2279.56     445 2283.76   474.3  2294.3   503.6 2302.89   513.4 2308.27
   581.8 2327.37   591.6 2332.62   601.4 2336.27   669.8 2357.75   689.4 2366.75
   699.2 2369.87   718.7  2373.2   767.6 2388.78   777.4 2393.01     836 2407.43
#Mann= 3 , 0 , 0
       0      .1       0   395.8    .045       0   415.8      .1       0
Bank Sta=395.8,415.8
XS Rating Curve= 0 ,0
Exp/Cntr=0.3,0.1

Type RM Length L Ch R = 1 ,16824.1 ,329.3,346.2,363.3
XS GIS Cut Line= 3
       1968562.4      157499.911     1968792.903      157767.369
     1969436.516      157680.605
#Sta/Elev= 30
       0  2412.3    78.5 2378.25    88.3 2378.05   147.1 2361.18   196.2 2351.52
   225.6 2349.47   264.8 2342.97   323.7 2336.78   353.1  2335.8     393 2340.78
     403 2339.51     463 2321.23     483 2312.72   542.9  2295.9   562.9 2287.67
   600.3 2276.64   612.8  2274.5   620.3 2274.62   632.8 2276.34   712.8 2303.34
   722.8 2310.21   802.7 2338.87   812.7  2346.9   822.7 2351.41   832.7 2355.42
   842.6 2355.82   852.6 2359.26   892.6 2374.04   912.6 2384.16  1002.5 2408.29
#Mann= 3 , 0 , 0
       0      .1       0   600.3    .045       0   620.3      .1       0
Bank Sta=600.3,620.3
XS Rating Curve= 0 ,0
Exp/Cntr=0.3,0.1

Type RM Length L Ch R = 1 ,16477.7 ,351.1,395.2,439.2
XS GIS Cut Line= 3
     1968529.754       157581.88     1968803.953      157977.016
     1969563.671      158409.453
#Sta/Elev= 30
       0 2365.44    39.3 2351.36    88.3 2337.88     108  2337.6     157 2326.48
   196.3 2320.14   245.4 2317.83   323.9 2310.27   343.5 2310.54   431.9 2305.33
     481 2304.78   510.8 2307.89   530.6 2307.75   600.2 2286.13     620 2278.29
   642.8 2273.31   649.8 2272.95   662.8 2273.74   749.2 2284.51   798.8  2298.5
   808.8 2299.73   848.5 2312.95     918 2343.51   967.7 2360.13   997.5 2363.86
  1166.4 2404.68  1176.3 2406.12  1196.2 2405.85  1265.7 2422.56  1355.1 2439.91
#Mann= 3 , 0 , 0
       0      .1       0   642.8    .045       0   662.8      .1       0
Bank Sta=642.8,662.8
XS Rating Curve= 0 ,0
Exp/Cntr=0.3,0.1

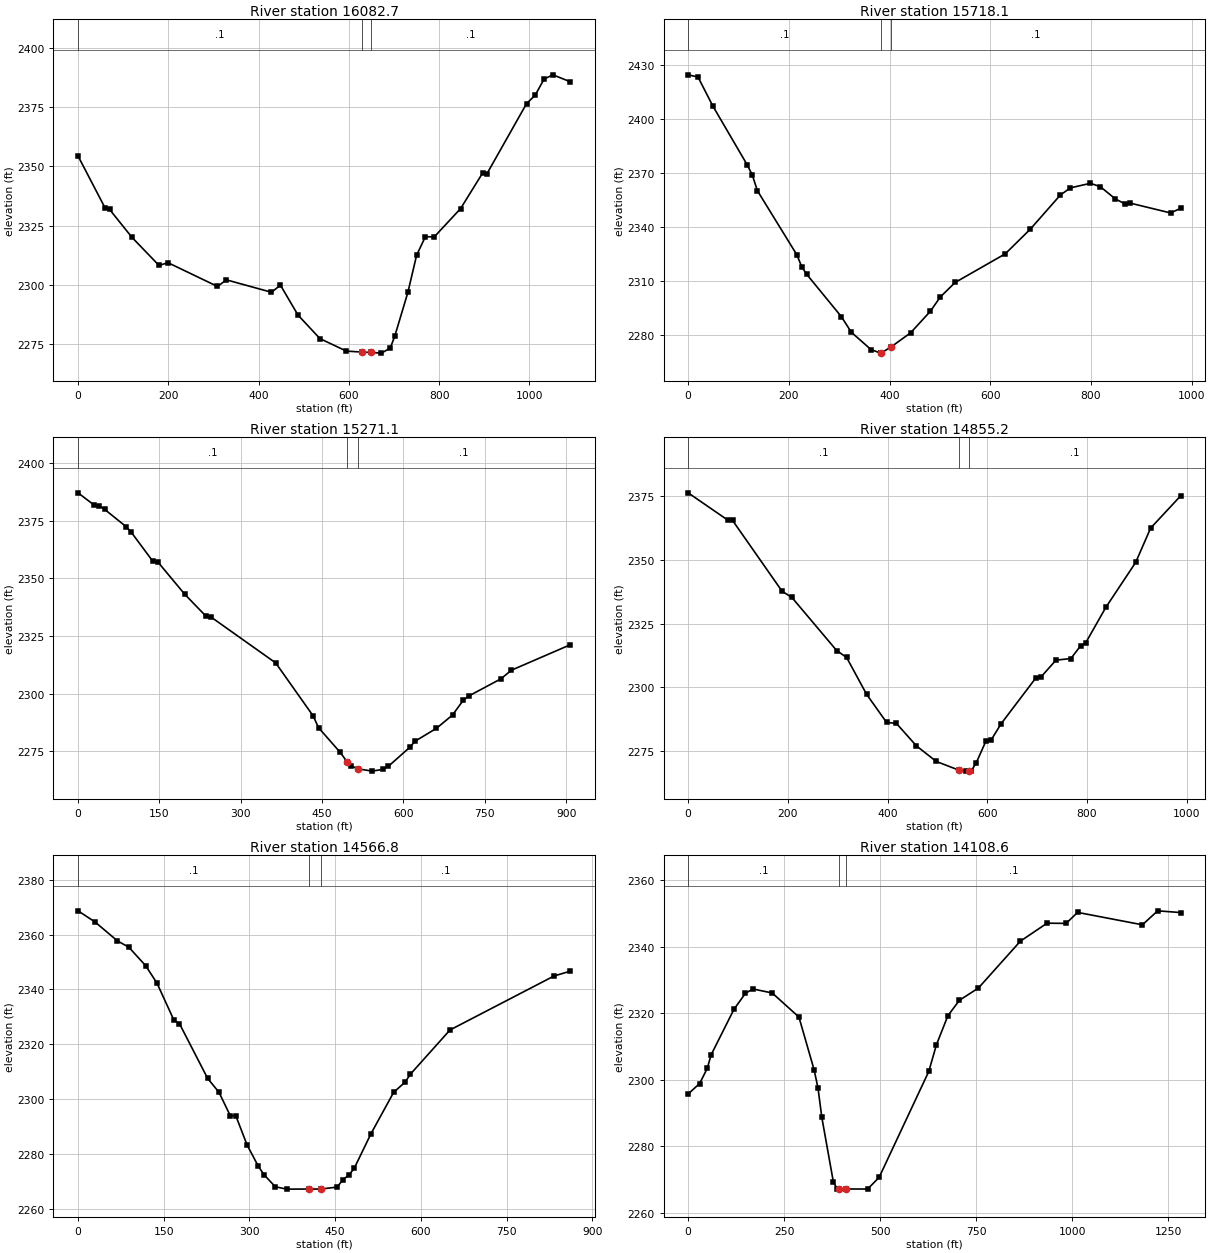
Type RM Length L Ch R = 1 ,16082.7 ,408.3,364.3,320.4
XS GIS Cut Line= 4
      1968458.94       157614.96     1968753.147      157953.386
     1968554.261      158229.912     1968711.794      158487.433
#Sta/Elev= 30
       0 2354.31    59.8 2332.49    69.8 2331.83   119.6 2320.03   179.4 2308.24
   199.3 2309.39   308.9 2299.39   328.8 2302.16   428.5 2296.94   448.4 2299.93
   487.4 2287.31     536 2277.42   594.4 2272.17   630.1 2271.73   650.1 2271.58
   672.3 2271.31   691.7 2273.46   701.5 2278.33   730.7 2296.85   750.1 2312.54
   769.6 2320.36     789 2320.22   847.5 2332.17   896.2 2347.11   905.9 2346.84
   993.6 2376.34    1013 2379.98  1032.5 2386.72    1052  2388.5  1090.9 2385.56
#Mann= 3 , 0 , 0
       0      .1       0   630.1    .045       0   650.1      .1       0
Bank Sta=630.1,650.1
XS Rating Curve= 0 ,0
Exp/Cntr=0.3,0.1

Type RM Length L Ch R = 1 ,15718.1 ,448.1,447,445.9
XS GIS Cut Line= 3
     1968058.336      157937.499     1968518.024      158181.419
     1968662.938      158615.498
#Sta/Elev= 30
       0 2424.37    19.6 2423.15    49.1 2407.01   117.8 2374.11   127.6 2368.56
   137.5    2360     216 2324.31   225.8 2317.61   235.6 2313.47   304.4 2289.96
     324 2281.35   363.3 2271.66   382.2 2269.73   382.9 2269.71   402.2 2272.99
   441.8 2280.98   481.1 2292.96   500.8  2300.9   530.3 2308.98   629.8 2324.88
   679.6  2338.6   739.3 2357.58   759.2 2361.54     799 2364.09   818.8 2362.18
   848.7 2355.36   868.6 2352.54   878.5 2353.04   958.1 2347.62     978 2350.15
#Mann= 3 , 0 , 0
       0      .1       0   382.2    .045       0   402.2      .1       0
Bank Sta=382.2,402.2
XS Rating Curve= 0 ,0
Exp/Cntr=0.3,0.1

Type RM Length L Ch R = 1 ,15271.1 ,383.3,415.6,448
XS GIS Cut Line= 3
     1967910.883      158191.207     1968000.518      158420.087
      1968600.13      158700.615
#Sta/Elev= 30
       0 2387.12    29.5 2381.84    39.3 2381.52    49.2 2379.91    88.5 2372.47
    98.3 2369.97   137.6 2357.51   147.5 2357.03   196.6 2343.15     236 2333.57
   245.8 2333.13   364.4 2313.34   433.5 2290.34   443.4 2285.24   482.9 2274.65
   496.2 2270.41   502.7 2268.69   516.2  2267.4   542.2  2266.4     562 2267.16
   571.9 2268.44   611.4 2276.69   621.3 2279.38   660.8 2284.97   690.4 2290.74
   710.2 2297.14   720.1 2298.96   779.4 2306.41   799.1 2310.18   907.8 2321.25
#Mann= 3 , 0 , 0
       0      .1       0   496.2    .045       0   516.2      .1       0
Bank Sta=496.2,516.2
XS Rating Curve= 0 ,0
Exp/Cntr=0.3,0.1

Type RM Length L Ch R = 1 ,14855.2 ,289.2,288.4,287.7
XS GIS Cut Line= 3
     1967833.608      158257.884     1967986.339      158453.169
     1967875.276      159184.531
#Sta/Elev= 30
       0 2376.35    79.3 2365.68    89.2  2365.5   188.4 2337.76   208.2  2335.3
   297.9  2314.5   317.9 2311.77   357.9 2297.35   397.9 2286.34   417.9 2285.88
   457.8 2277.12   497.8 2270.99   542.8  2267.6   557.8  2267.2   562.8 2267.24
   567.8 2267.29   577.8 2270.42   597.8 2279.21   607.8 2279.42   627.8 2285.79
   697.8 2303.85   707.8 2304.13   737.8 2310.73   767.7 2311.35   787.7 2316.46
   797.7  2317.6   837.7 2331.38   897.7 2349.06   927.7 2362.52   987.7 2375.12
#Mann= 3 , 0 , 0
       0      .1       0   542.8    .045       0   562.8      .1       0
Bank Sta=542.8,562.8
XS Rating Curve= 0 ,0
Exp/Cntr=0.3,0.1

Type RM Length L Ch R = 1 ,14566.8 ,487.1,457.9,428.7
XS GIS Cut Line= 3
     1967722.999       158245.75     1967635.427      158930.504
     1967650.126       159101.23
#Sta/Elev= 30
       0 2368.65    29.6 2364.61      69 2357.68    88.8  2355.4   118.3 2348.65
   138.1 2342.31   167.6 2328.87   177.5  2327.5   226.8 2307.55   246.6  2302.5
   266.3    2294   276.1 2293.93   295.9 2283.24   315.6 2275.47   325.4 2272.43
   345.2 2268.04   364.9 2267.17   404.8  2267.2   424.8  2267.2   453.6 2267.92
   463.5 2270.63   473.4 2272.17   483.2 2274.71   512.8 2287.44   552.3 2302.46
     572 2306.12   581.8 2309.12   650.9  2325.2   833.1  2344.9   861.7 2346.66
#Mann= 3 , 0 , 0
       0      .1       0   404.8    .045       0   424.8      .1       0
Bank Sta=404.8,424.8
XS Rating Curve= 0 ,0
Exp/Cntr=0.3,0.1

Type RM Length L Ch R = 1 ,14108.6 ,524.1,547,570
XS GIS Cut Line= 3
     1966957.022      158556.322     1967556.265      158910.418
     1967783.118      159450.374
#Sta/Elev= 30
       0 2295.76    29.8 2298.88    49.7 2303.44    59.7 2307.49   119.3  2321.2
   149.2 2326.03     169 2327.31   218.8 2326.11   288.4 2318.87   328.1 2302.93
   338.1 2297.47     348  2288.7   377.8 2269.45   387.8 2267.16   391.7 2267.18
   411.7  2267.2   467.3 2267.19   497.2 2270.71   626.4 2302.54   646.3 2310.56
   676.2 2319.29     706  2323.9   755.6  2327.6   864.8 2341.68   934.3 2347.09
   983.9 2347.02  1013.7 2350.33  1182.4  2346.6  1222.2  2350.8  1281.7 2350.28
#Mann= 3 , 0 , 0
       0      .1       0   391.7    .045       0   411.7      .1       0
Bank Sta=391.7,411.7
XS Rating Curve= 0 ,0
Exp/Cntr=0.3,0.1

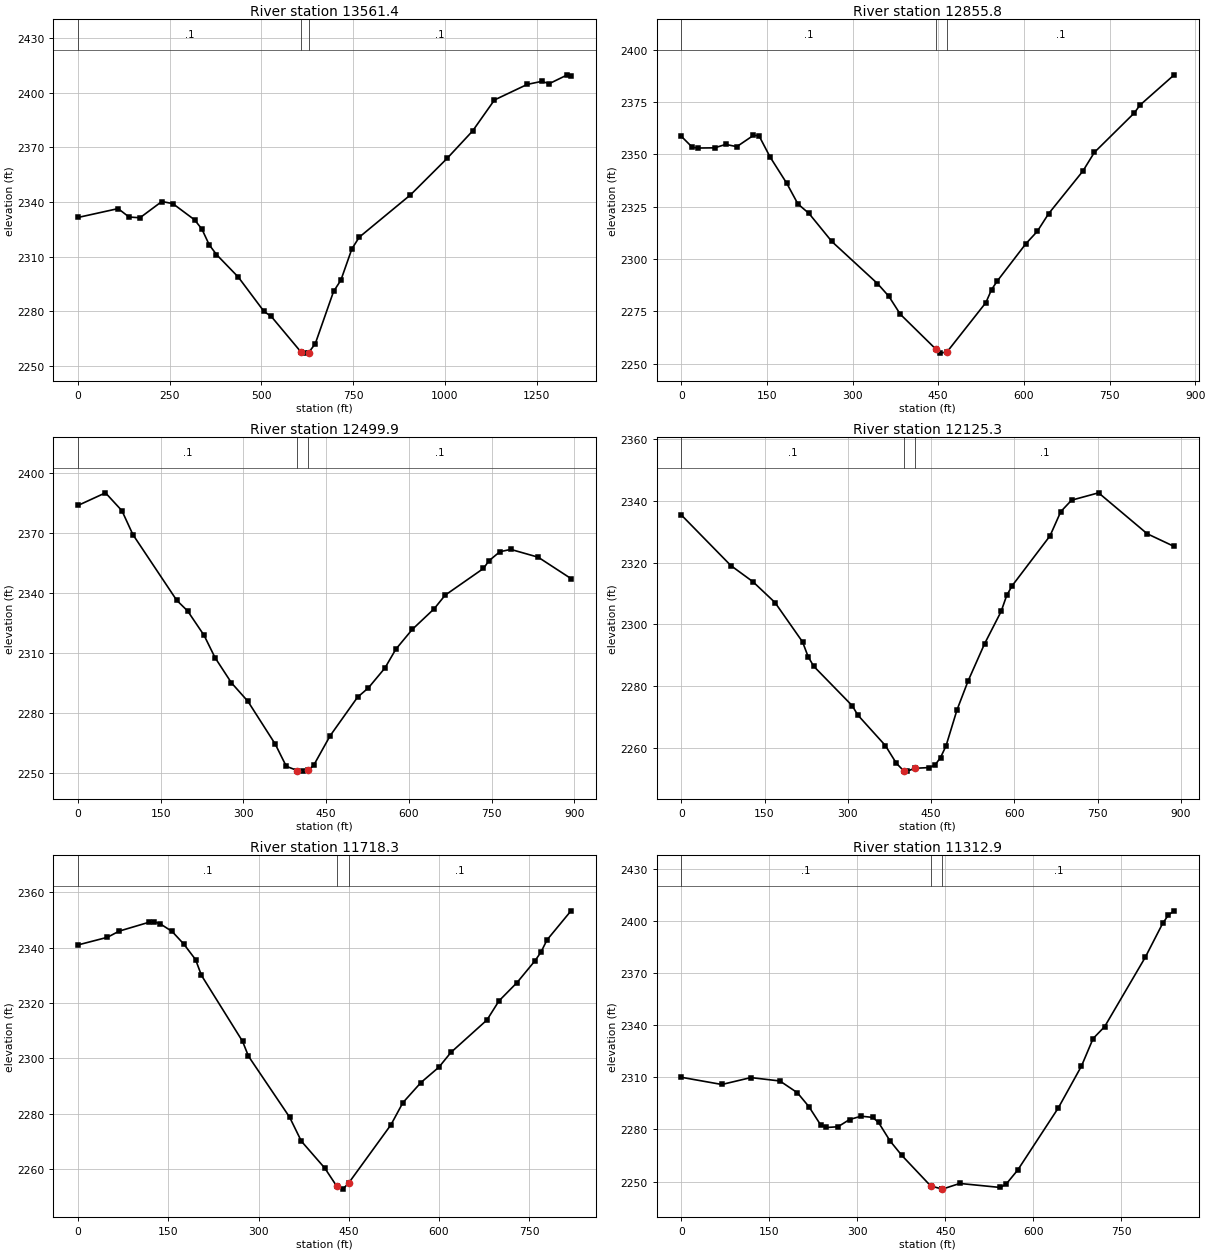
Type RM Length L Ch R = 1 ,13561.4 ,736.1,705.6,675.2
XS GIS Cut Line= 4
     1966586.236      158630.398     1966920.607       158926.96
     1966985.157      159442.305     1967256.159      159705.582
#Sta/Elev= 30
       0 2331.48   109.2 2336.34     139 2331.71   168.8 2331.31   228.4 2340.24
   258.2  2339.1   317.8 2330.15   337.7 2325.07   357.6 2316.45   377.4  2311.1
     437 2298.68   506.9 2279.85   526.8 2277.08   608.4 2257.39   616.7 2256.92
   628.4 2257.16   646.7 2262.05   696.6 2290.79   716.6 2297.01   746.6 2314.22
   766.6 2320.62   906.4 2343.89  1006.1 2363.91  1075.7 2378.99  1135.3 2396.04
  1224.8  2404.6  1264.6 2406.28  1284.5 2404.98  1334.2 2409.86  1344.1 2409.18
#Mann= 3 , 0 , 0
       0      .1       0   608.4    .045       0   628.4      .1       0
Bank Sta=608.4,628.4
XS Rating Curve= 0 ,0
Exp/Cntr=0.3,0.1

Type RM Length L Ch R = 1 ,12855.8 ,335.9,355.8,375.6
XS GIS Cut Line= 3
      1966207.27      159314.446     1966366.473      159471.641
     1966988.693      159619.489
#Sta/Elev= 30
       0 2358.71    19.4 2353.42    29.2 2353.08    58.4 2353.17    77.8  2354.8
    97.3 2353.74   126.5 2359.14   136.2 2358.93   155.6 2348.78   184.8  2336.2
   204.3 2326.36   223.7 2321.81   263.7 2308.41   343.6 2288.32   363.6  2282.2
   383.6 2273.65   445.4  2257.1   453.6 2255.06   465.4 2255.62   533.5 2279.21
   543.5 2285.46   553.5 2289.55   603.5 2307.34   623.4 2313.21   643.4 2321.72
   703.4 2342.07   723.4 2350.96   793.3  2369.8   803.3 2373.57   863.3 2388.06
#Mann= 3 , 0 , 0
       0      .1       0   445.4    .045       0   465.4      .1       0
Bank Sta=445.4,465.4
XS Rating Curve= 0 ,0
Exp/Cntr=0.3,0.1

Type RM Length L Ch R = 1 ,12499.9 ,410.4,374.5,338.7
XS GIS Cut Line= 3
     1966139.302      159404.195     1966432.638      159888.718
     1966734.369      160016.258
#Sta/Elev= 30
       0 2383.78    49.7 2390.06    79.5 2381.15    99.4 2369.24   178.9 2336.43
   198.7  2331.1   228.6  2318.9   248.4 2307.81   278.2 2295.22     308 2286.01
   357.7  2264.6   377.6 2253.59   397.8 2251.45   407.4 2251.17   417.8 2251.76
   427.3 2254.07   457.1  2268.8   506.8 2288.04   526.6 2292.74   556.5 2302.62
   576.3 2312.02   606.1 2321.89   645.8 2332.19   665.7 2338.98   735.2 2352.31
   745.1 2356.12   764.9 2360.66   784.8 2361.82   834.4 2357.94     894 2347.26
#Mann= 3 , 0 , 0
       0      .1       0   397.8    .045       0   417.8      .1       0
Bank Sta=397.8,417.8
XS Rating Curve= 0 ,0
Exp/Cntr=0.3,0.1

Type RM Length L Ch R = 1 ,12125.3 ,395.2,407,418.2
XS GIS Cut Line= 3
     1965894.526       160194.02     1966446.816      159970.243
     1966708.229       160099.58
#Sta/Elev= 30
       0 2335.43    89.4 2319.02   129.1  2313.8   168.8 2307.07   218.5 2294.31
   228.4 2289.56   238.4 2286.47   307.9 2273.67   317.8 2270.68   367.5 2260.79
   387.3 2255.06   400.2 2252.67   407.2 2252.51   420.2 2253.42   446.9 2253.67
   456.9 2254.49   466.8 2256.88   476.7 2260.66   496.6 2272.37   516.4 2281.66
   546.2 2293.74     576  2304.2     586 2309.37   595.9 2312.52     664 2328.65
   683.4  2336.5   702.8 2340.19   751.4 2342.57     839 2329.32   887.6 2325.21
#Mann= 3 , 0 , 0
       0      .1       0   400.2    .045       0   420.2      .1       0
Bank Sta=400.2,420.2
XS Rating Curve= 0 ,0
Exp/Cntr=0.3,0.1

Type RM Length L Ch R = 1 ,11718.3 ,387.9,405.4,423.2
XS GIS Cut Line= 3
     1965905.479      160393.121     1966313.126      160439.418
     1966721.678      160465.193
#Sta/Elev= 30
       0 2340.97    48.8 2343.72    68.4 2345.96   117.2 2349.11     127 2349.29
   136.8 2348.56   156.3 2345.84   175.8 2341.27   195.4 2335.65   205.1 2329.98
   273.5 2306.12   283.3 2300.75   351.7 2278.71   371.2 2270.04   410.3 2260.27
   430.2 2253.71   440.2  2252.7   450.2 2254.98   520.1 2275.92   540.1 2283.96
     570 2291.21     600 2296.79   619.9 2302.11   679.8 2313.83   699.8 2320.73
   729.8 2327.35   759.7 2335.23   769.7 2338.39   779.7 2342.78   819.6 2353.29
#Mann= 3 , 0 , 0
       0      .1       0   430.2    .045       0   450.2      .1       0
Bank Sta=430.2,450.2
XS Rating Curve= 0 ,0
Exp/Cntr=0.3,0.1

Type RM Length L Ch R = 1 ,11312.9 ,362.2,369.4,376.9
XS GIS Cut Line= 3
     1965859.678      160499.141      1966170.75      160803.274
     1966462.777      161083.879
#Sta/Elev= 30
       0 2310.04    69.2 2305.89   118.6 2309.86   168.1 2307.91   197.8 2301.16
   217.5 2293.15   237.3 2282.74   247.2 2281.13     267 2281.54   286.7 2285.69
   306.5 2287.64   326.3 2286.93   336.2 2284.01   355.9 2273.35   375.7 2265.11
     425 2247.49   444.9 2245.64     445 2245.65   474.6 2248.91   543.7 2246.59
   553.6 2248.52   573.3  2256.6   642.5 2292.39     682 2316.51   701.8 2332.34
   721.5 2339.21   790.6 2379.07   820.3 2398.61   830.2 2403.51     840 2405.88
#Mann= 3 , 0 , 0
       0      .1       0     425    .045       0     445      .1       0
Bank Sta=425,445
XS Rating Curve= 0 ,0
Exp/Cntr=0.3,0.1

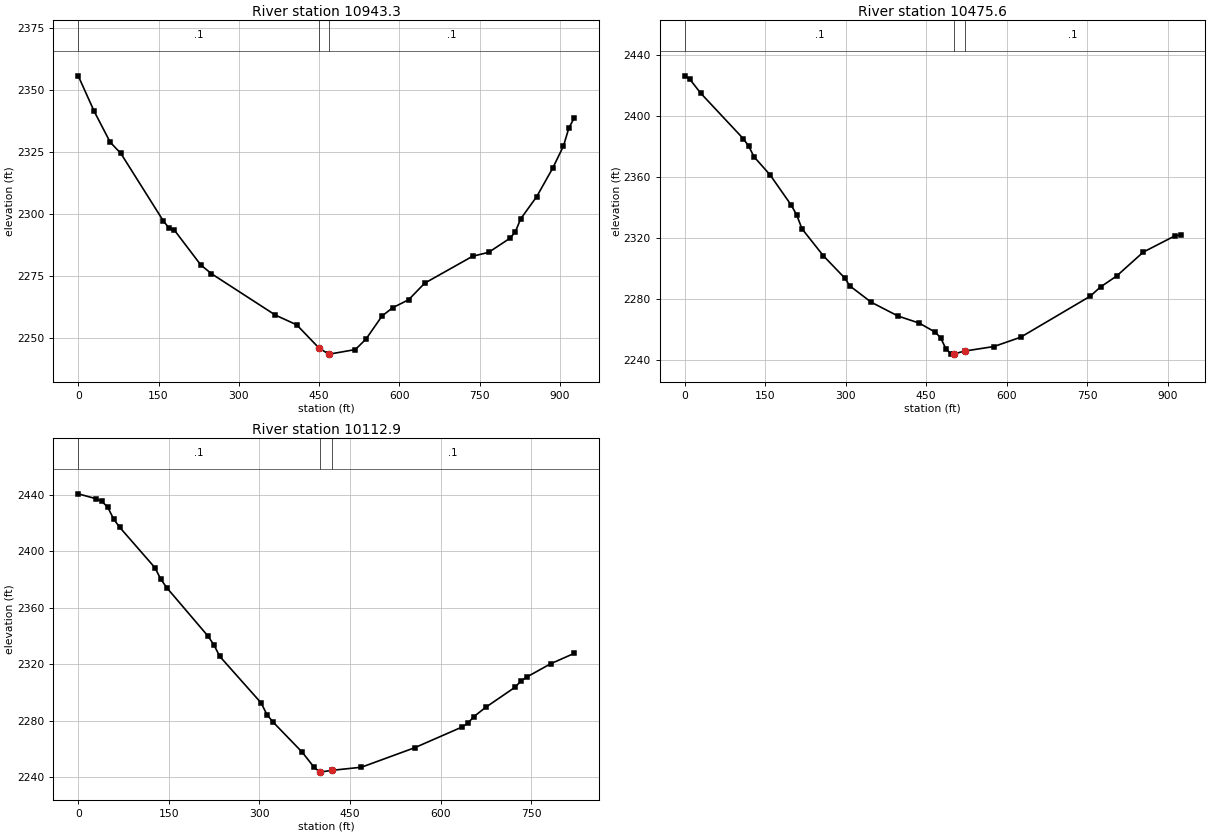
Type RM Length L Ch R = 1 ,10943.3 ,483,467.8,452.5
XS GIS Cut Line= 3
      1965618.57      160552.734     1966009.653      161258.102
      1966118.72      161308.059
#Sta/Elev= 30
       0 2355.83    29.9 2341.46    59.7 2329.03    79.7 2324.48   159.3 2297.13
   169.3 2294.48   179.2 2293.64     229 2279.45   248.9 2275.92   368.4  2259.2
   408.2 2255.27   449.4 2245.99     468 2243.44   469.4 2243.45   517.8 2245.29
   537.7 2249.54   567.6 2258.84   587.5 2262.18   617.3 2265.41   647.2 2272.08
   736.8 2282.97   766.7 2284.54   806.5 2290.22   816.5 2292.75   826.5 2298.03
   856.5 2307.03   886.5 2318.56   906.5 2327.46   916.5 2334.69   926.5 2338.78
#Mann= 3 , 0 , 0
       0      .1       0   449.4    .045       0   469.4      .1       0
Bank Sta=449.4,469.4
XS Rating Curve= 0 ,0
Exp/Cntr=0.3,0.1

Type RM Length L Ch R = 1 ,10475.6 ,368.3,362.7,356.6
XS GIS Cut Line= 2
     1965164.865      161111.593     1965990.444      161526.789
#Sta/Elev= 30
       0 2426.49     9.9 2424.11    29.8 2415.11   109.3 2385.19   119.2 2380.38
   129.2 2373.34     159 2361.52   198.7 2341.51   208.7 2335.16   218.6 2326.05
   258.4 2308.35   298.1  2293.8     308 2288.48   347.8 2277.82   397.5 2268.79
   437.2 2264.12     467 2258.18     477 2254.44   486.9 2247.17   496.8 2243.78
   501.9 2243.95   521.9  2245.8   576.3 2248.77     626 2254.87   755.2 2281.71
     775  2287.9   804.9 2295.07   854.6 2310.78   914.2 2321.56   924.1 2321.86
#Mann= 3 , 0 , 0
       0      .1       0   501.9    .045       0   521.9      .1       0
Bank Sta=501.9,521.9
XS Rating Curve= 0 ,0
Exp/Cntr=0.3,0.1

Type RM Length L Ch R = 1 ,10112.9 ,399.6,424.3,449.6
XS GIS Cut Line= 3
     1965053.619      161561.059     1965452.434      161656.531
     1965853.797      161744.134
#Sta/Elev= 30
       0 2440.49    29.3 2437.05    39.1 2435.14    48.8 2431.09    58.6 2422.68
    68.4 2416.96   126.9 2388.31   136.7 2380.19   146.5 2374.16   214.8 2339.93
   224.6 2333.73   234.3 2325.58   302.7  2292.7   312.4 2284.43   322.2 2279.28
     371 2257.73   390.6 2247.07   400.1 2243.75   420.1 2245.02   468.8 2247.22
   556.8 2260.98     635 2275.57   644.8 2278.26   654.6 2282.87   674.2 2289.48
   723.1 2303.77   732.9 2308.19   742.6    2311   781.8 2320.31   820.9  2327.7
#Mann= 3 , 0 , 0
       0      .1       0   400.1    .045       0   420.1      .1       0
Bank Sta=400.1,420.1
XS Rating Curve= 0 ,0
Exp/Cntr=0.3,0.1