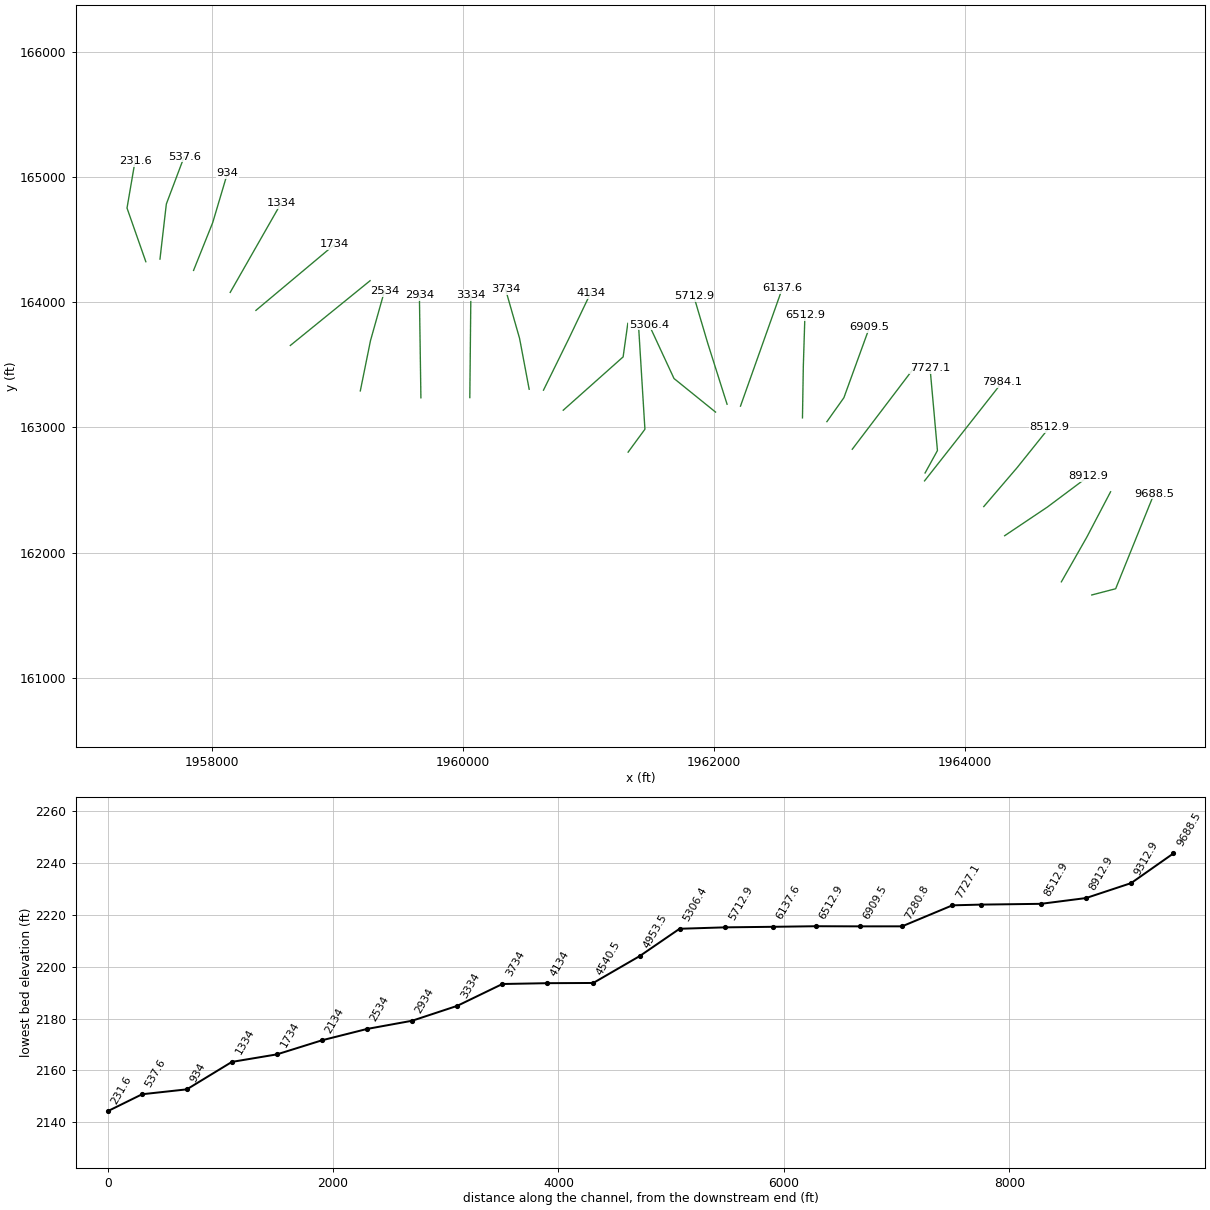
HEC-RAS study LrlCrk2.prj: LrlCrk2

--- LrlCrk2.g01 (geometry) --- (continued)

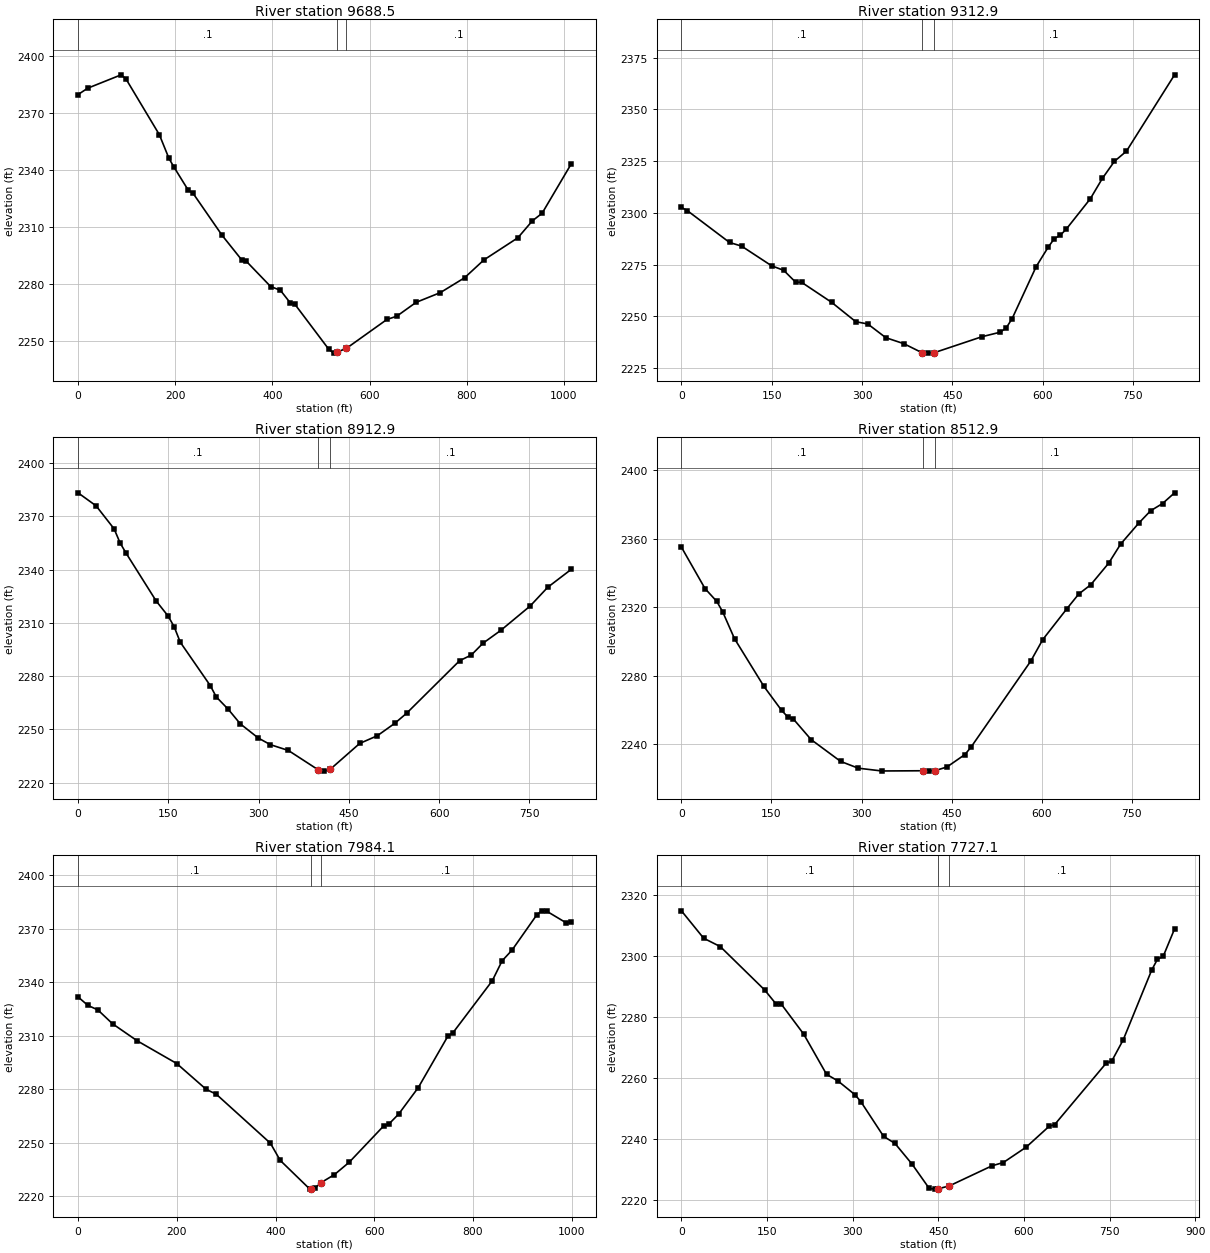
Type RM Length L Ch R = 1 ,9688.5  ,379,375.7,373.2
XS GIS Cut Line= 3
     1965013.402      161660.861     1965203.855      161710.625
      1965509.87      162469.162
#Sta/Elev= 30
       0 2379.83    19.7 2383.16    88.6 2390.21    98.4 2388.12   167.3  2358.7
     187 2346.26   196.8 2341.88   226.8 2329.48   236.8  2327.8   296.6 2305.68
   336.5 2292.92   346.5 2292.04   396.3 2278.81   416.3 2276.85   436.2 2270.37
   446.2 2269.47     516 2245.78     526 2243.77   532.2 2244.25   552.2 2246.27
   635.7  2261.5   655.7 2263.17   695.6 2270.48   745.5 2275.61   795.3  2283.4
   835.2 2292.82   905.1 2304.47     935  2313.4   954.9 2317.35  1014.8  2343.3
#Mann= 3 , 0 , 0
       0      .1       0   532.2    .045       0   552.2      .1       0
Bank Sta=532.2,552.2
XS Rating Curve= 0 ,0
Exp/Cntr=0.3,0.1

Type RM Length L Ch R = 1 ,9312.9  ,411.6,400,388.8
XS GIS Cut Line= 3
     1964771.221      161765.842     1964973.492      162121.838
     1965163.379      162484.993
#Sta/Elev= 30
       0 2302.66      10 2301.08    79.9 2285.75    99.9 2283.99   149.8 2274.48
   169.8 2272.31   189.7 2266.57   199.7 2266.49   249.7  2256.8   289.6 2247.48
   309.6 2246.38   339.5 2239.76   369.5 2236.86   399.4 2232.54   409.4  2232.3
   419.4 2232.46   499.4 2240.24   529.4  2242.4   539.4 2244.41   549.4 2248.99
   589.4 2274.14   609.4 2283.53   619.4 2287.58   629.3 2289.22   639.3 2292.19
   679.3 2306.87   699.3  2316.7   719.3 2324.94   739.3 2329.85   819.2 2366.72
#Mann= 3 , 0 , 0
       0      .1       0   399.4    .045       0   419.4      .1       0
Bank Sta=399.4,419.4
XS Rating Curve= 0 ,0
Exp/Cntr=0.3,0.1

Type RM Length L Ch R = 1 ,8912.9  ,393.2,400,406.3
XS GIS Cut Line= 3
     1964319.272      162133.999      1964659.02      162362.402
     1964987.292      162608.285
#Sta/Elev= 30
       0 2383.29      30 2375.95    59.9 2362.99    69.9 2355.02    79.9 2349.24
   129.8 2322.37   149.8 2313.81   159.8 2307.76   169.8 2299.17   219.7 2274.71
   229.7 2268.32   249.6 2261.35   269.6 2253.16   299.6 2245.15   319.5 2241.45
   349.5 2238.17   399.4  2227.2   409.4 2226.53   419.4 2227.66     468 2242.12
   497.3 2246.46   526.6 2253.53   546.1 2259.17     634 2288.71   653.5 2291.93
     673  2298.6   702.4 2305.79   751.2  2319.5   780.5 2330.08   819.5 2340.16
#Mann= 3 , 0 , 0
       0      .1       0   399.4    .045       0   419.4      .1       0
Bank Sta=399.4,419.4
XS Rating Curve= 0 ,0
Exp/Cntr=0.3,0.1

Type RM Length L Ch R = 1 ,8512.9  ,527.3,528.6,529.1
XS GIS Cut Line= 3
     1964152.769      162366.659      1964420.64      162680.164
     1964676.063      162999.595
#Sta/Elev= 30
       0 2355.17    39.3 2330.98    58.9 2323.48    68.7 2317.41    88.4  2301.7
   137.4 2273.82   166.9 2259.78   176.7 2256.14   186.5 2254.72     216 2242.73
   265.1    2230   294.5 2226.02   333.8 2224.39   402.4 2224.52   412.4  2224.3
   422.4 2224.58   442.3 2226.73   472.2    2234   482.2 2238.23   581.9 2288.62
   601.9  2301.2   641.8 2319.11   661.8 2327.81   681.7 2333.19   711.6  2345.8
   731.6 2356.99   761.5 2369.13   781.4 2376.44   801.4  2380.7   821.4 2386.95
#Mann= 3 , 0 , 0
       0      .1       0   402.4    .045       0   422.4      .1       0
Bank Sta=402.4,422.4
XS Rating Curve= 0 ,0
Exp/Cntr=0.3,0.1

Type RM Length L Ch R = 1 ,7984.1  ,238,257.1,276.2
XS GIS Cut Line= 2
     1963680.874      162571.954     1964297.628      163357.666
#Sta/Elev= 30
       0 2331.68      20 2326.92      40 2324.43    69.9 2316.63   119.9 2307.08
   199.8 2294.38   259.7 2279.86   279.7 2277.24   389.6 2249.72   409.5  2240.1
   469.5    2224   472.5 2224.14   479.4 2224.47   492.5 2227.69   519.4 2232.15
   549.4  2239.1   619.3 2259.48   629.3 2260.38   649.3 2266.01   689.2 2280.92
   749.2 2309.76   759.1 2311.51     839 2340.73     859 2351.93     879 2357.89
   928.9 2377.55   938.9 2379.93   948.9 2379.79   988.9 2373.17   998.9 2373.67
#Mann= 3 , 0 , 0
       0      .1       0   472.5    .045       0   492.5      .1       0
Bank Sta=472.5,492.5
XS Rating Curve= 0 ,0
Exp/Cntr=0.3,0.1

Type RM Length L Ch R = 1 ,7727.1  ,464.5,446.1,427.7
XS GIS Cut Line= 3
     1963685.306        162635.2     1963783.666      162814.166
     1963724.831       163471.23
#Sta/Elev= 30
       0 2314.97    38.9 2305.99    68.1 2303.24   145.9    2289   165.3 2284.53
     175 2284.36   214.2 2274.54   254.2 2261.37   274.2 2259.19   304.2 2254.65
   314.2 2252.43   354.1 2241.04   374.1  2238.7   404.1  2231.9   434.1 2223.95
   444.1 2223.72     449 2223.81     469 2224.75   544.1 2231.37     564 2232.45
     604 2237.49     644 2244.29     654 2244.91     744    2265     754 2265.75
     774 2272.69   823.9 2295.57   833.9 2299.08   843.9    2300   863.9 2309.04
#Mann= 3 , 0 , 0
       0      .1       0     449    .045       0     469      .1       0
Bank Sta=449,469
XS Rating Curve= 0 ,0
Exp/Cntr=0.3,0.1

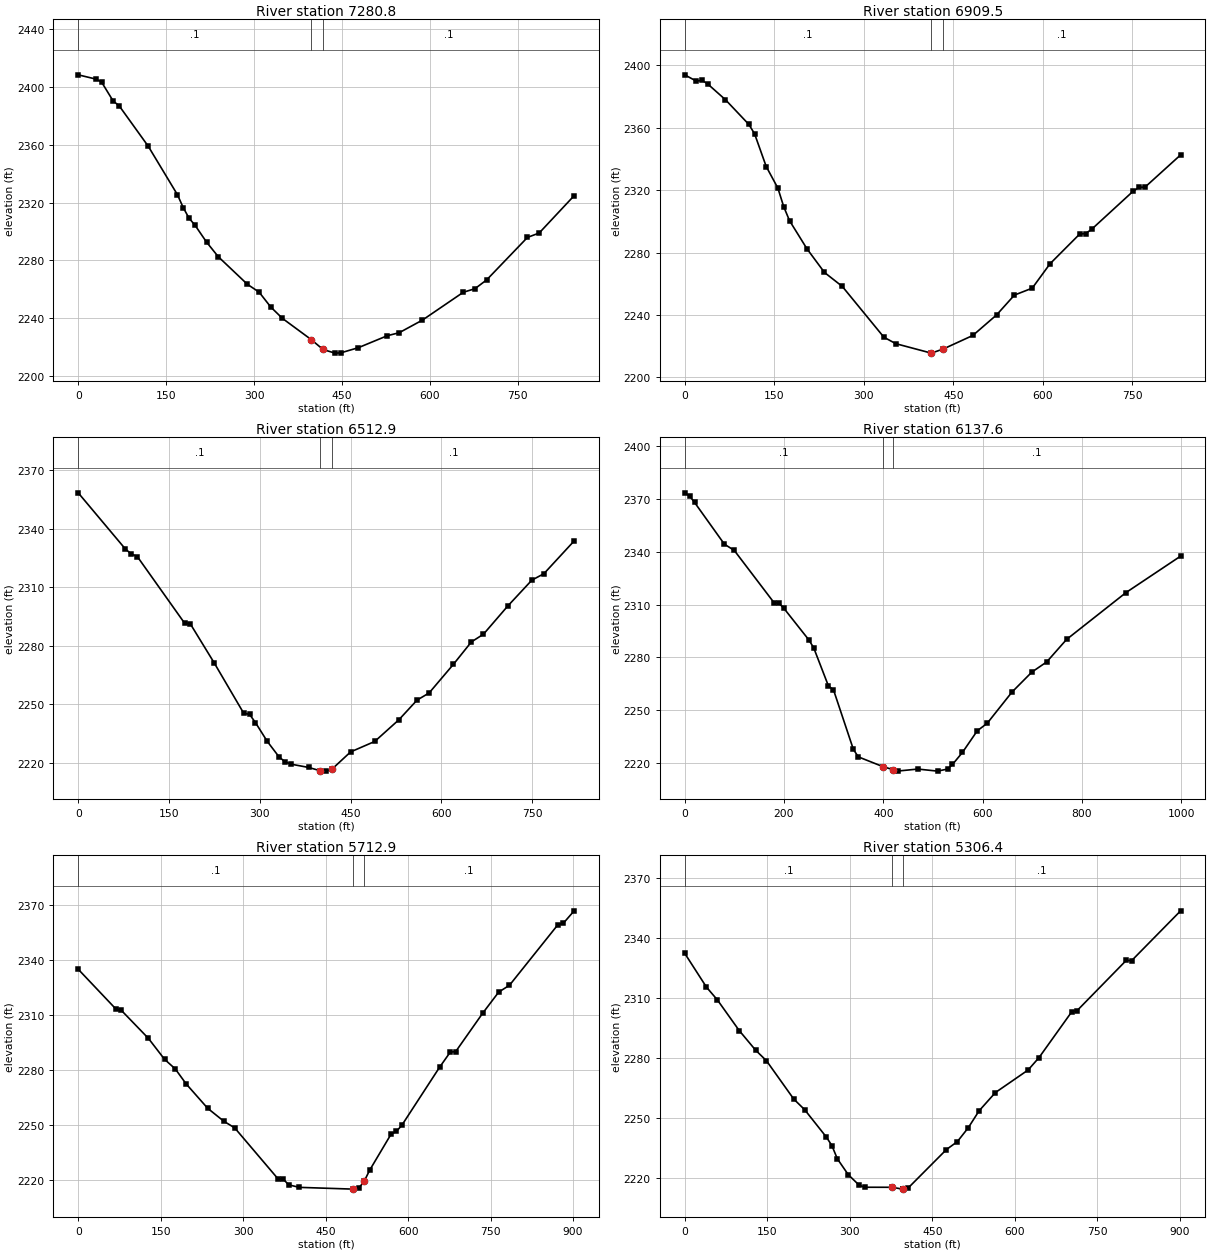
Type RM Length L Ch R = 1 ,7280.8  ,363.9,371.3,378.8
XS GIS Cut Line= 2
     1963104.908      162824.712     1963615.789      163498.904
#Sta/Elev= 30
       0 2408.49    29.9 2405.56    39.8 2403.51    59.7 2390.28    69.7  2387.1
   119.4 2359.02   169.2 2325.44   179.1 2316.48   189.1 2309.08     199 2304.39
   218.9 2292.57   238.8 2282.47   288.6  2263.3   308.5  2257.9   328.4 2247.58
   348.3 2239.69   397.6 2224.94   417.6 2218.13   437.9 2215.61   447.8  2215.8
   477.7 2219.36   527.4 2227.71   547.3 2229.72   587.2 2238.52   656.8 2257.79
   676.7 2260.26   696.6 2266.34   766.3 2295.83   786.2 2298.83   845.9 2324.74
#Mann= 3 , 0 , 0
       0      .1       0   397.6    .045       0   417.6      .1       0
Bank Sta=397.6,417.6
XS Rating Curve= 0 ,0
Exp/Cntr=0.3,0.1

Type RM Length L Ch R = 1 ,6909.5  ,388.3,396.6,404.5
XS GIS Cut Line= 3
      1962902.66      163044.862     1963038.126       163235.97
     1963241.408      163796.902
#Sta/Elev= 30
       0 2394.02    19.5 2389.99    29.3  2390.5      39 2388.02    68.3 2378.06
   107.4 2362.27   117.1 2356.23   136.6 2335.23   156.2 2321.35   165.9 2309.51
   175.7 2300.49     205 2282.41   234.2 2267.32   264.1 2258.35   333.7 2225.83
   353.6 2221.67   413.2  2215.6   433.2 2218.24   482.8 2226.94   522.6 2240.11
   552.4  2252.8   582.3 2257.26   612.1 2272.88   661.8 2291.94   671.8 2292.28
   681.7 2294.95   751.3 2319.39   761.3 2321.95   771.2 2321.99   830.9 2342.69
#Mann= 3 , 0 , 0
       0      .1       0   413.2    .045       0   433.2      .1       0
Bank Sta=413.2,433.2
XS Rating Curve= 0 ,0
Exp/Cntr=0.3,0.1

Type RM Length L Ch R = 1 ,6512.9  ,383.4,375.3,367.5
XS GIS Cut Line= 3
     1962708.045      163075.063     1962714.795      163485.054
     1962727.607      163894.164
#Sta/Elev= 30
       0 2358.32    78.1 2329.45    87.9 2326.96    97.6 2325.66   175.7 2291.52
   185.5 2291.01   224.6 2271.18   273.4 2245.34   283.1 2244.75   292.9 2240.51
   312.4 2230.88   331.9 2222.92   341.7 2220.44   351.5 2219.23   380.8 2217.53
     400 2215.84     410 2215.65     420 2216.87     450 2225.49   489.9 2230.86
   529.8 2241.97   559.8 2252.05   579.8 2255.73   619.7 2270.32   649.6 2281.89
   669.6 2285.85   709.5 2300.21   749.5 2313.55   769.4 2316.86   819.4 2333.66
#Mann= 3 , 0 , 0
       0      .1       0     400    .045       0     420      .1       0
Bank Sta=400,420
XS Rating Curve= 0 ,0
Exp/Cntr=0.3,0.1

Type RM Length L Ch R = 1 ,6137.6  ,408.3,424.5,440.3
XS GIS Cut Line= 2
     1962214.198      163168.973     1962547.794      164110.296
#Sta/Elev= 30
       0  2373.4      10 2371.55      20 2367.91    79.9 2344.27    99.9  2340.7
   179.8 2311.08   189.8 2310.76   199.7 2307.88   249.7 2290.04   259.7 2285.52
   289.6  2263.7   299.6 2261.64   339.6 2227.86   349.5 2223.54   400.3 2217.86
   420.3 2216.24   429.4 2215.48   469.4  2216.6   509.3 2215.43   529.3 2216.61
   539.3 2219.22   559.3 2226.02   589.2 2238.32   609.2 2242.58   659.1  2260.3
   699.1 2271.64     729 2277.41     769 2290.17   888.8  2316.8   998.7 2337.47
#Mann= 3 , 0 , 0
       0      .1       0   400.3    .045       0   420.3      .1       0
Bank Sta=400.3,420.3
XS Rating Curve= 0 ,0
Exp/Cntr=0.3,0.1

Type RM Length L Ch R = 1 ,5712.9  ,391.6,406.4,421.7
XS GIS Cut Line= 3
     1962107.135       163184.08     1961953.317      163670.573
      1961842.21      164046.207
#Sta/Elev= 30
       0  2334.9    68.7  2313.2    78.5 2312.51   127.6  2297.3     157 2285.89
   176.6 2280.63   196.2 2272.54   235.5 2259.21   264.9 2252.16   284.6 2248.56
     363 2220.95   372.9 2220.69   382.7 2217.56   402.3 2216.18   500.2 2215.22
   510.2 2215.74   520.2 2219.51   529.8 2225.38     569 2245.14   578.8 2246.69
   588.6 2249.98   657.1 2281.49   676.7 2289.81   686.5 2290.06   735.5 2310.92
   764.8 2322.48   784.4 2326.19   872.6  2359.2   882.4 2359.96     902  2366.7
#Mann= 3 , 0 , 0
       0      .1       0   500.2    .045       0   520.2      .1       0
Bank Sta=500.2,520.2
XS Rating Curve= 0 ,0
Exp/Cntr=0.3,0.1

Type RM Length L Ch R = 1 ,5306.4  ,373.6,352.8,332.1
XS GIS Cut Line= 3
     1962015.355      163121.345     1961684.278      163389.542
     1961484.636      163820.613
#Sta/Elev= 30
       0 2332.53    39.6 2315.59    59.4 2309.22    99.1  2293.9   128.8 2284.13
   148.6 2278.82   198.2 2259.67     218 2254.36   257.6 2240.62   267.5 2236.41
   277.4 2229.81   297.3 2221.87   317.1 2216.62     327 2215.61   376.5 2215.59
   396.4 2214.67   396.5 2214.68   406.3 2215.31   475.6 2234.45   495.4  2238.4
   515.2 2245.31   534.9 2253.79   564.6 2262.93     624  2274.2   643.8 2280.39
   703.2 2303.25   713.1 2303.89   802.2 2328.94   812.1 2328.84   901.1 2353.73
#Mann= 3 , 0 , 0
       0      .1       0   376.5    .045       0   396.5      .1       0
Bank Sta=376.5,396.5
XS Rating Curve= 0 ,0
Exp/Cntr=0.3,0.1

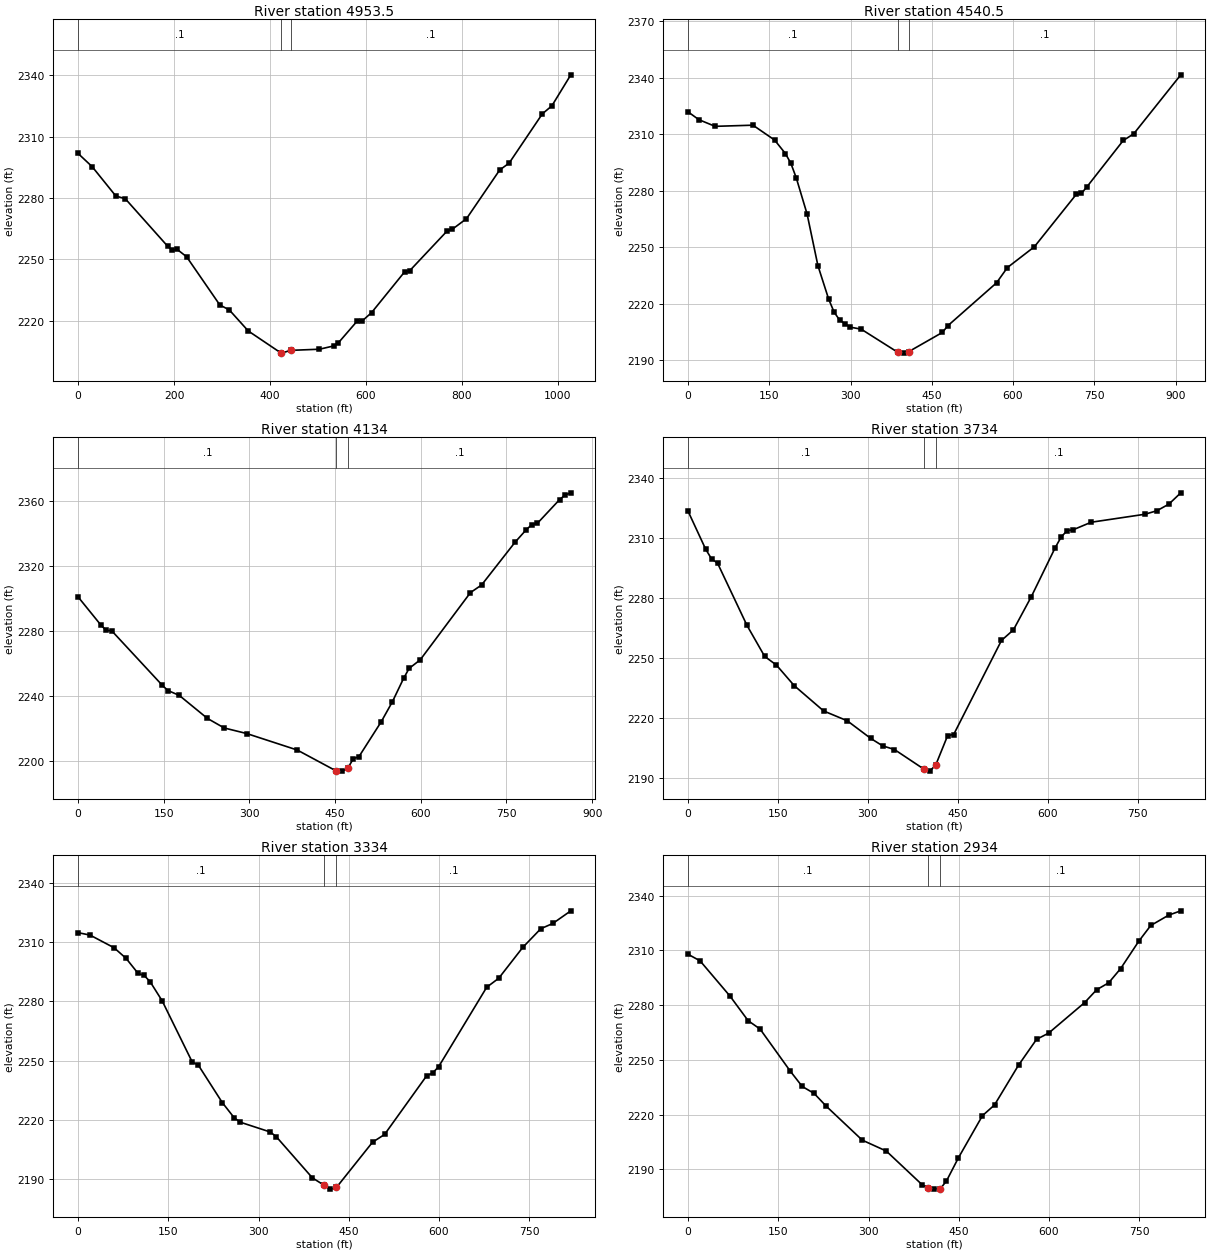
Type RM Length L Ch R = 1 ,4953.5  ,435.9,413,390.1
XS GIS Cut Line= 3
     1961318.858      162801.789     1961452.524      162984.306
     1961403.467      163783.403
#Sta/Elev= 30
       0 2301.76    29.5 2295.27    78.7 2280.95    98.4 2279.62   186.9 2256.35
   196.7 2254.38   206.6 2254.85   226.2 2251.25   295.4  2227.7   315.2 2225.26
   354.7 2214.98   422.8 2204.23   423.9 2204.15   442.8  2205.5     503 2206.06
   532.6 2207.66   542.5  2209.2     582 2219.92   591.9 2219.84   611.7 2223.98
   680.9 2244.01   690.8 2244.36   769.8 2264.05   779.7 2264.68   809.4 2269.86
   878.6 2293.68   898.3 2297.04   967.5 2321.13   987.3 2325.03  1026.8 2340.19
#Mann= 3 , 0 , 0
       0      .1       0   422.8    .045       0   442.8      .1       0
Bank Sta=422.8,442.8
XS Rating Curve= 0 ,0
Exp/Cntr=0.3,0.1

Type RM Length L Ch R = 1 ,4540.5  ,396.6,406.4,416.4
XS GIS Cut Line= 3
     1960801.721       163136.36      1961278.84       163562.07
     1961316.263      163829.602
#Sta/Elev= 30
       0 2321.95      20  2317.8      50 2314.25   119.9 2314.86   159.9 2306.95
   179.8 2299.78   189.8 2294.64   199.8 2286.89   219.8 2267.67   239.8 2240.21
   259.8 2222.28   269.8 2215.47   279.8 2211.33   289.7 2209.33   299.7 2207.53
   319.7 2206.47   387.3 2194.17   399.6 2193.74   407.3  2194.5   469.6 2204.74
   479.6  2208.3   569.5 2231.09   589.5 2239.19   639.4 2250.27   716.6 2278.08
   726.3 2278.66   735.9 2281.94   803.4 2306.73   822.7 2310.26   909.6 2341.62
#Mann= 3 , 0 , 0
       0      .1       0   387.3    .045       0   407.3      .1       0
Bank Sta=387.3,407.3
XS Rating Curve= 0 ,0
Exp/Cntr=0.3,0.1

Type RM Length L Ch R = 1 ,4134    ,383.8,400,418.2
XS GIS Cut Line= 3
     1960644.242      163296.495     1960848.062      163711.532
     1961020.109      164072.827
#Sta/Elev= 30
       0 2301.16    39.4 2284.02    49.2 2280.48      59 2280.22   147.6 2246.56
   157.4 2243.37   177.1  2240.4   226.3 2226.22   255.8 2220.29   295.1 2216.86
   383.7 2206.68   452.4 2193.68   462.4 2193.66   472.4 2195.64   481.9  2201.3
   491.7 2202.59   530.7 2224.12   550.2 2236.42   569.8 2250.84   579.5 2257.01
     599 2262.33   686.9  2303.8   706.4 2308.49     765 2334.88   784.5 2342.56
   794.2 2345.71     804  2346.5     843 2361.18   852.8 2364.04   862.6 2365.34
#Mann= 3 , 0 , 0
       0      .1       0   452.4    .045       0   472.4      .1       0
Bank Sta=452.4,472.4
XS Rating Curve= 0 ,0
Exp/Cntr=0.3,0.1

Type RM Length L Ch R = 1 ,3734    ,405,400,392.6
XS GIS Cut Line= 3
     1960530.167      163303.714     1960453.688      163709.859
     1960341.402      164102.969
#Sta/Elev= 30
       0 2323.33    29.5 2304.25    39.4 2299.39    49.2 2297.35    98.4 2266.18
   127.9 2250.69   147.6 2246.33   177.1  2236.1   226.3 2223.41   265.7  2218.5
     305 2209.66   324.7 2205.98   344.4 2204.14   393.6 2194.33   403.3 2193.34
   413.3 2196.41   433.2 2211.14   443.2 2211.64     523 2258.69   542.9 2263.96
   572.8 2280.58   612.7 2305.11   622.7 2310.46   632.7  2313.6   642.6    2314
   672.5 2317.75   762.3 2321.75   782.2  2323.5   802.2  2326.8   822.1 2332.46
#Mann= 3 , 0 , 0
       0      .1       0   393.6    .045       0   413.3      .1       0
Bank Sta=393.6,413.3
XS Rating Curve= 0 ,0
Exp/Cntr=0.3,0.1

Type RM Length L Ch R = 1 ,3334    ,399.4,400,400.6
XS GIS Cut Line= 3
     1960057.185      163237.172     1960061.364      163646.651
     1960065.543      164056.129
#Sta/Elev= 30
       0 2314.86      20 2313.62    59.9  2307.2    79.9 2301.81    99.9 2294.17
   109.9 2293.18   119.8    2290   139.8 2280.31   189.8  2249.3   199.8 2247.78
   239.7 2228.77   259.7 2220.99   269.7 2218.81   319.6 2213.84   329.6 2211.42
   389.5 2190.61   409.5 2186.77   419.5 2184.91   429.5 2185.78   489.4 2208.68
   509.4 2212.59   579.3  2242.3   589.3 2243.74   599.3 2246.94   679.2  2287.2
   699.2 2291.76   739.1 2307.38   769.1 2316.86     789 2319.51     819 2325.92
#Mann= 3 , 0 , 0
       0      .1       0   409.5    .045       0   429.5      .1       0
Bank Sta=409.5,429.5
XS Rating Curve= 0 ,0
Exp/Cntr=0.3,0.1

Type RM Length L Ch R = 1 ,2934    ,405.3,400,392.7
XS GIS Cut Line= 3
     1959667.423      163235.359     1959661.401      163644.815
      1959655.38      164054.271
#Sta/Elev= 30
       0 2307.94      20 2304.34    69.9 2284.95    99.9 2271.53   119.8 2266.92
   169.8 2243.93   189.8 2235.46   209.7 2231.61   229.7 2224.64   289.6 2206.02
   329.6 2200.03   389.5 2181.44   399.5 2179.84   409.5 2179.16   419.5 2179.45
   429.5  2183.6   449.4 2196.31   489.4 2219.45   509.4  2225.3   549.3 2247.11
   579.3 2261.29   599.3 2264.68   659.2 2281.44   679.2 2288.48   699.2 2292.29
   719.1  2300.1   749.1 2315.04   769.1 2323.71     799  2329.4     819 2331.75
#Mann= 3 , 0 , 0
       0      .1       0   399.5    .045       0   419.5      .1       0
Bank Sta=399.5,419.5
XS Rating Curve= 0 ,0
Exp/Cntr=0.3,0.1

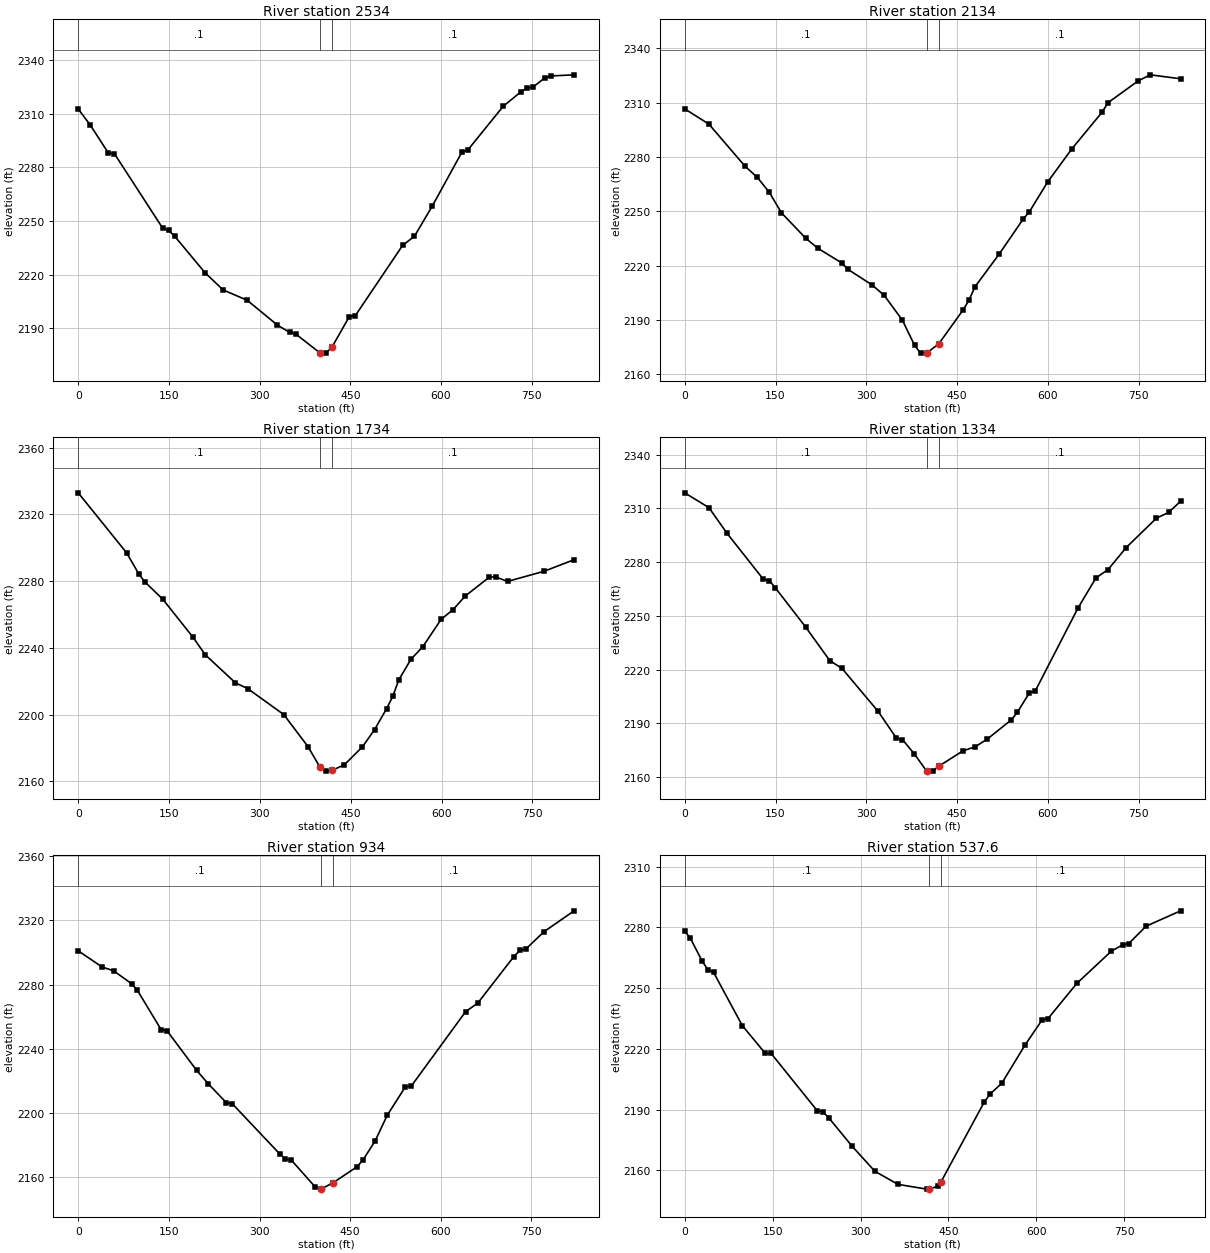
Type RM Length L Ch R = 1 ,2534    ,417.2,399.9,384.5
XS GIS Cut Line= 3
     1959184.476      163290.184     1959265.516      163691.335
     1959376.686      164086.899
#Sta/Elev= 30
       0 2312.65      20 2303.64    49.9 2287.98    59.9 2287.62   139.8 2245.88
   149.7 2244.67   159.7 2241.35   209.6 2221.04   239.6 2211.38   279.5 2205.57
   329.4 2191.68   349.4 2187.64   359.4  2186.8   399.3  2176.2   409.3 2175.99
   419.3 2179.19   448.4 2196.44   458.2 2196.98   536.4 2236.28     556 2241.42
   585.4 2258.25   634.3 2288.37     644  2289.6   702.8 2314.18   732.1 2322.26
   741.9  2324.3   751.7  2324.8   771.2    2330     781 2331.14   820.1 2331.78
#Mann= 3 , 0 , 0
       0      .1       0   399.3    .045       0   419.3      .1       0
Bank Sta=399.3,419.3
XS Rating Curve= 0 ,0
Exp/Cntr=0.3,0.1

Type RM Length L Ch R = 1 ,2134    ,399.6,400,400.3
XS GIS Cut Line= 3
     1958627.113      163653.457     1958944.674      163912.022
     1959262.427      164170.346
#Sta/Elev= 30
       0 2306.53      40 2298.08    99.9 2274.74   119.9 2268.68   139.8 2260.42
   159.8  2249.1   199.8 2235.09   219.7 2229.57   259.7 2221.36   269.7 2217.87
   309.6 2209.23   329.6 2203.48   359.6 2189.76   379.6 2175.95   389.5 2171.61
   399.5 2171.65   419.5 2176.69   459.4 2195.28   469.4 2200.75   479.4 2208.24
   519.4 2226.32   559.3 2245.77   569.3  2249.7   599.3 2266.08   639.2 2284.35
   689.2 2304.63   699.2 2309.92   749.1 2322.02   769.1 2325.31     819 2323.12
#Mann= 3 , 0 , 0
       0      .1       0   399.5    .045       0   419.5      .1       0
Bank Sta=399.5,419.5
XS Rating Curve= 0 ,0
Exp/Cntr=0.3,0.1

Type RM Length L Ch R = 1 ,1734    ,390.9,399.8,408.7
XS GIS Cut Line= 3
     1958352.679      163933.506     1958666.345      164196.763
     1958980.011      164460.019
#Sta/Elev= 30
       0 2332.94    79.9    2297    99.9 2284.42   109.9 2279.61   139.8 2269.12
   189.8  2246.3   209.7 2235.92   259.7 2219.07   279.7 2215.68   339.6 2200.02
   379.5 2180.82   399.5 2168.37   409.5 2166.17   419.5 2166.66   439.5 2169.97
   469.4 2180.74   489.4 2191.05   509.4 2203.67   519.4  2210.9   529.4 2220.86
   549.3  2233.1   569.3 2240.84   599.3 2257.12   619.2    2263   639.2 2271.11
   679.2 2282.48   689.2 2282.54   709.1 2279.86   769.1  2285.9     819 2292.88
#Mann= 3 , 0 , 0
       0      .1       0   399.5    .045       0   419.5      .1       0
Bank Sta=399.5,419.5
XS Rating Curve= 0 ,0
Exp/Cntr=0.3,0.1

Type RM Length L Ch R = 1 ,1334    ,396.5,400,405.7
XS GIS Cut Line= 3
     1958147.789      164077.155     1958350.404      164433.016
      1958553.02      164788.877
#Sta/Elev= 30
       0 2318.65      40 2310.39    69.9 2296.07   129.8 2270.41   139.8 2269.69
   149.8 2265.57   199.8 2243.69   239.7 2224.94   259.7 2220.66   319.6 2196.56
   349.6 2181.69   359.6 2180.87   379.5 2172.79   399.5 2163.31   409.5 2163.26
   419.5 2165.96   459.4 2174.56   479.4  2176.8   499.4 2181.06   539.3 2191.85
   549.3 2196.07   569.3 2206.99   579.3 2208.24   649.2 2254.14   679.2 2271.17
   699.2 2275.78   729.1  2288.1     779 2304.48     799 2307.68     819 2313.94
#Mann= 3 , 0 , 0
       0      .1       0   399.5    .045       0   419.5      .1       0
Bank Sta=399.5,419.5
XS Rating Curve= 0 ,0
Exp/Cntr=0.3,0.1

Type RM Length L Ch R = 1 ,934     ,389.8,396.4,398.4
XS GIS Cut Line= 3
       1957855.7       164252.69     1958008.508      164634.868
     1958125.002      165027.063
#Sta/Elev= 30
       0 2300.99    39.2 2290.98    58.8 2288.48    88.2 2280.53      98 2276.34
   137.2 2251.93     147 2251.23     196 2226.55   215.6 2218.05     245  2206.5
   254.8 2205.86   333.2 2174.66     343 2171.44   352.8 2170.67     392 2154.09
   401.6 2152.66   421.6 2156.58   461.5 2166.61   471.5 2170.94   491.4 2182.68
   511.4 2198.66   541.3 2216.26   551.3 2216.86   641.1 2263.14   661.1  2268.4
   720.9 2297.39   730.9 2301.24   740.9 2302.13   770.8  2312.9   820.7 2325.87
#Mann= 3 , 0 , 0
       0      .1       0   401.6    .045       0   421.6      .1       0
Bank Sta=401.6,421.6
XS Rating Curve= 0 ,0
Exp/Cntr=0.3,0.1

Type RM Length L Ch R = 1 ,537.6   ,294.7,306,319.7
XS GIS Cut Line= 3
       1957588.1      164343.232     1957638.773      164782.852
      1957780.89      165160.448
#Sta/Elev= 30
       0 2278.27     9.8 2274.59    29.5  2263.5    39.3 2259.19    49.2 2257.84
    98.3  2231.5   137.7 2217.75   147.5 2217.75   226.2 2189.46     236  2188.9
   245.8 2185.99   285.2 2172.08   324.5 2159.56   363.9 2153.12     413 2150.77
   416.8 2150.82   432.7 2152.22   436.8 2154.12   511.4 2193.96   521.2 2197.77
   540.9 2203.03   580.3 2221.79   609.8 2234.36   619.7 2234.94   668.9 2252.34
   727.9 2268.28   747.6 2271.45   757.4 2271.97   786.9 2280.57     846 2288.18
#Mann= 3 , 0 , 0
       0      .1       0   416.8    .045       0   436.8      .1       0
Bank Sta=416.8,436.8
XS Rating Curve= 0 ,0
Exp/Cntr=0.3,0.1

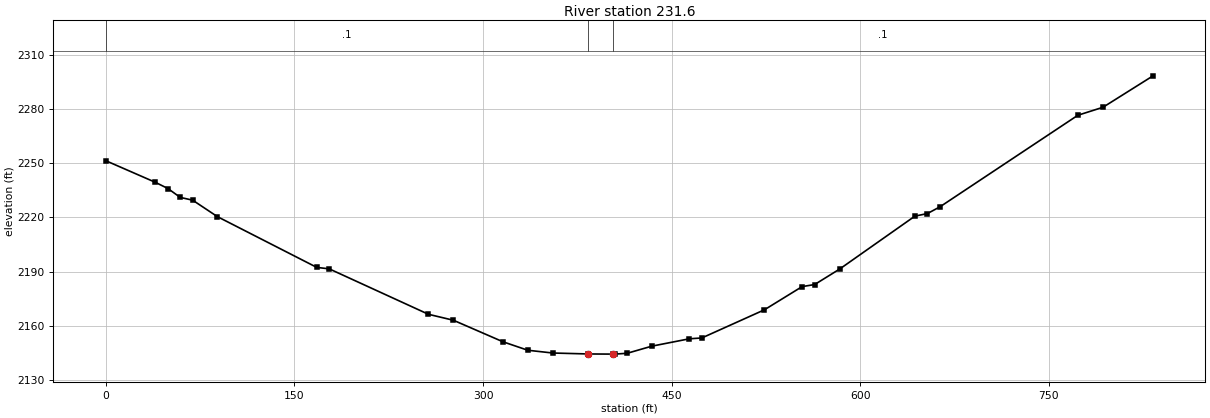
Type RM Length L Ch R = 1 ,231.6   ,256,231.5,207
XS GIS Cut Line= 3
     1957475.388      164322.091     1957325.468      164750.681
      1957389.27      165124.042
#Sta/Elev= 30
       0 2251.44    39.5 2239.43    49.4 2236.02    59.2  2231.1    69.1 2229.55
    88.8 2220.41   167.8 2192.29   177.7 2191.48   256.6 2166.29   276.4    2163
   315.9 2151.04   335.6 2146.36   355.4 2144.83   383.7  2144.3   403.7 2144.22
   404.7 2144.21   414.6 2144.68   434.3 2148.64     464  2152.7     474 2153.18
   523.8  2168.8   553.7 2181.63   563.7 2182.79   583.6 2191.38   643.4  2220.7
   653.4 2222.15   663.4 2225.89     773 2276.63     793 2281.06   832.8 2298.49
#Mann= 3 , 0 , 0
       0      .1       0   383.7    .045       0   403.7      .1       0
Bank Sta=383.7,403.7
XS Rating Curve= 0 ,0
Exp/Cntr=0.3,0.1

Chan Stop Cuts=-1
Use User Specified Reach Order=0
Composite Channel Slope=5